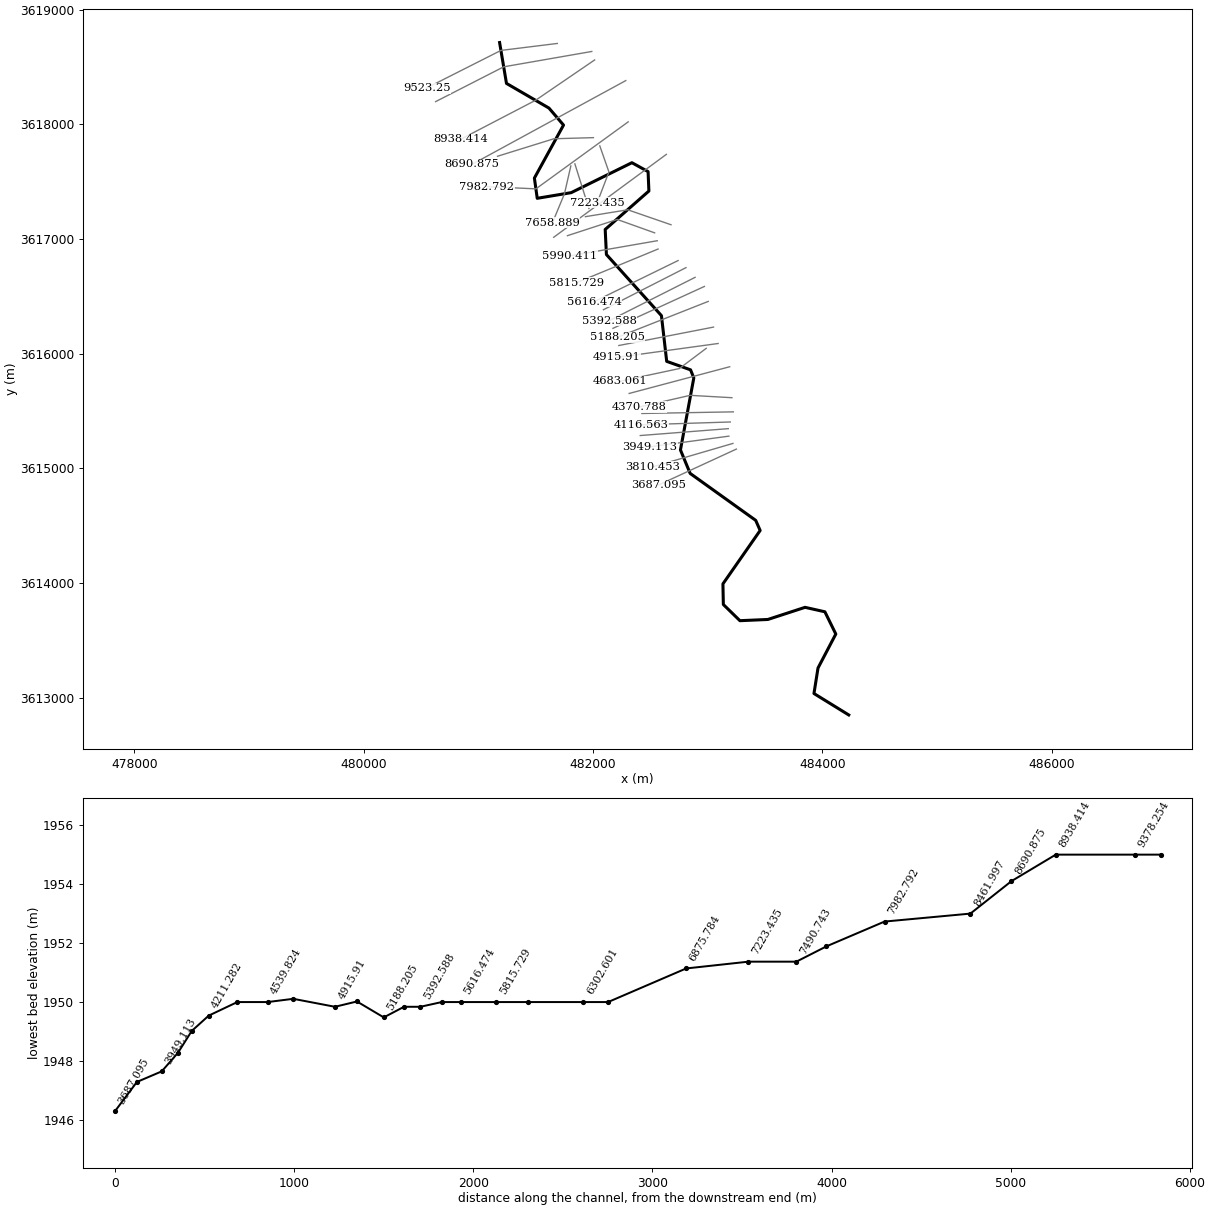
--- Flood.prj (project) ---

Proj Title=Flood
Current Plan=p01
Default Exp/Contr=0.3,0.1
SI Units
Geom File=g01
Flow File=f01
Plan File=p01
Y Axis Title=Elevation
X Axis Title(PF)=Main Channel Distance
X Axis Title(XS)=Station
BEGIN DESCRIPTION:
END DESCRIPTION:
DSS Export Rating Curves= 0
DSS Export Rating Curve Sorted= 0
DSS Export Volume Flow Curves= 0
DXF OffsetX= 0
DXF OffsetY= 0
DXF ScaleX= 1
DXF ScaleY= 10

--- Flood.p01 (plan) ---

Plan Title=plan1
Program Version=4.10
Short Identifier=Steady
Geom File=g01
Flow File=f01
Mixed Flow
K Sum by GR= 0
Std Step Tol= 0.003
Critical Tol= 0.003
Num of Std Step Trials= 20
Max Error Tol= 0.1
Flow Tol Ratio= 0.001
Split Flow NTrial= 30
Split Flow Tol= 0.006
Split Flow Ratio= 0.02
Log Output Level= 0
Friction Slope Method= 1
Unsteady Friction Slope Method= 2
Unsteady Bridges Friction Slope Method= 1
Parabolic Critical Depth
Global Vel Dist= 0 , 0 , 0
Global Log Level= 0
CheckData=True
Encroach Param=-1 ,0,0, 0
Computation Interval=1HOUR
Output Interval=1HOUR
Run HTab= 0
Run UNet= 0
Run PostProcess= 0
Run WQNet= 0
UNET Theta= 1
UNET Theta Warmup= 1
UNET ZTol= 0.006
UNET ZSATol= 0.015
UNET MxIter= 20
UNET MaxInSteps= 0
UNET DtIC= 0
UNET DtMin= 0
UNET MaxCRTS= 20
UNET WFStab= 2
UNET SFStab= 1
UNET WFX= 1
UNET SFX= 1
UNET DSS MLevel= 4
UNET DZMax Abort= 30
UNET Convert EG Bridges= 0
UNET Use Existing IB Tables=-1
UNET Froude Reduction=False
UNET Froude Limit= 1
UNET Froude Power= 10
UNET Time Slicing=0,0, 5
UNET Junction Losses=0
Instantaneous Interval=1HOUR
Write IC File= 0
Write IC File at Sim End=0
Echo Input=False
Echo Parameters=False
Echo Output=False
Write Detailed= 0
WQ AD Non Conservative
WQ ULTIMATE=-1
WQ Max Comp Step=1HOUR
WQ Output Interval=15MIN
WQ Output Selected Increments= 0
WQ Output face flow=0
WQ Output face velocity=0
WQ Output face area=0
WQ Output face dispersion=0
WQ Output cell volume=0
WQ Output cell surface area=0
WQ Output cell continuity=0
WQ Output cumulative cell continuity=0
WQ Output face conc=0
WQ Output face dconc_dx=0
WQ Output face courant=0
WQ Output face peclet=0
WQ Output face adv mass=0
WQ Output face disp mass=0
WQ Output cell mass=0
WQ Output cell source sink temp=0
WQ Output cell source sink nsm=0
WQ Output MaxMinRange=-1
WQ Daily Max Min Mean=-1
WQ Daily Range=0
WQ Daily Time=0
WQ Create Restart=0
WQ Fixed Restart=0
WQ System Summary=0
WQ Use Fixed Temperature=0
Sorting and Armoring Iterations= 10
XS Update Threshold= 0.02
Hydraulics Update Threshold= 0.02
Energy Slope Method= 1
Volume Change Method= 0
XS Weighting Method= 0
Number of US Weighted Cross Sections= 1
Number of DS Weighted Cross Sections= 1
Upstream XS Weight=0.25
Main XS Weight=0.5
Downstream XS Weight=0.25
Number of DS XS's Weighted with US Boundary= 1
Upstream Boundary Weight= 1
Weight of XSs Associated with US Boundary= 0
Number of US XS's Weighted with DS Boundary= 1
Downstream Boundary Weight= 0.5
Weight of XSs Associated with DS Boundary= 0.5
Sediment Output Level= 4
Mass or Volume Output= 0
Output Increment Type= 1
Profile and TS Output Increment= 10
XS Output Flag= 0
XS Output Increment= 10
Disregard all LS=0
Disregard all Conn=0
Disregard all Breaches=0
Disregard all Pumps=0

--- Flood.f01 (steady flow) ---

Flow Title=myflow
Program Version=4.10
Number of Profiles= 8
Profile Names=PF 1,PF 2,PF 3,PF 4,PF 5,PF 6,PF 7,PF 8
River Rch & RM=Zayande_rood,Mainreach       ,9523.25
    71.5   102.8  129.83  174.69  218.07  272.05   339.3  454.33
Boundary for River Rch & Prof#=Zayande_rood,Mainreach       , 1
Up Type= 3
Up Slope=0.0171
Dn Type= 3
Dn Slope=0.00211
Boundary for River Rch & Prof#=Zayande_rood,Mainreach       , 2
Up Type= 3
Up Slope=0.0171
Dn Type= 3
Dn Slope=0.00211
Boundary for River Rch & Prof#=Zayande_rood,Mainreach       , 3
Up Type= 3
Up Slope=0.0171
Dn Type= 3
Dn Slope=0.00211
Boundary for River Rch & Prof#=Zayande_rood,Mainreach       , 4
Up Type= 3
Up Slope=0.0171
Dn Type= 3
Dn Slope=0.00211
Boundary for River Rch & Prof#=Zayande_rood,Mainreach       , 5
Up Type= 3
Up Slope=0.0171
Dn Type= 3
Dn Slope=0.00211
Boundary for River Rch & Prof#=Zayande_rood,Mainreach       , 6
Up Type= 3
Up Slope=0.0171
Dn Type= 3
Dn Slope=0.00211
Boundary for River Rch & Prof#=Zayande_rood,Mainreach       , 7
Up Type= 3
Up Slope=0.0171
Dn Type= 3
Dn Slope=0.00211
DSS Import GetInterval= 0
DSS Import GetPeak= 0
DSS Import FillOption= 0

--- Flood.g01 (geometry) ---

Geom Title=my_geo
Program Version=4.10

River Reach=Zayande_rood    ,Mainreach
Reach XY= 30
      481185.716    3618712.6383     481245.6883     3618356.332
     481616.1057    3618141.1371      481743.106    3617992.9702
     481489.1055    3617530.8303        481513.8    3617354.4411
     481810.1339    3617403.8301     482339.3016    3617664.8862
      482480.413    3617587.2749     482487.4686    3617417.9412
     482106.4678    3617082.8017     482117.0512     3616864.079
     482596.8299    3616331.3835     482642.6911    3615932.7438
     482850.8304    3615858.6603     482879.0527    3615788.1046
     482762.6358    3615160.1589     482847.3026    3614955.5474
     483418.8038    3614546.3244     483457.6094    3614458.1298
     483133.0532    3613992.4622      483136.581    3613812.5451
     483281.2202    3613671.4337     483524.6373    3613682.0171
     483849.1935    3613787.8506      484022.055     3613749.045
     484117.3052    3613555.0168     483962.0826    3613258.6829
     483926.8048    3613036.4325     484230.1943    3612849.4599

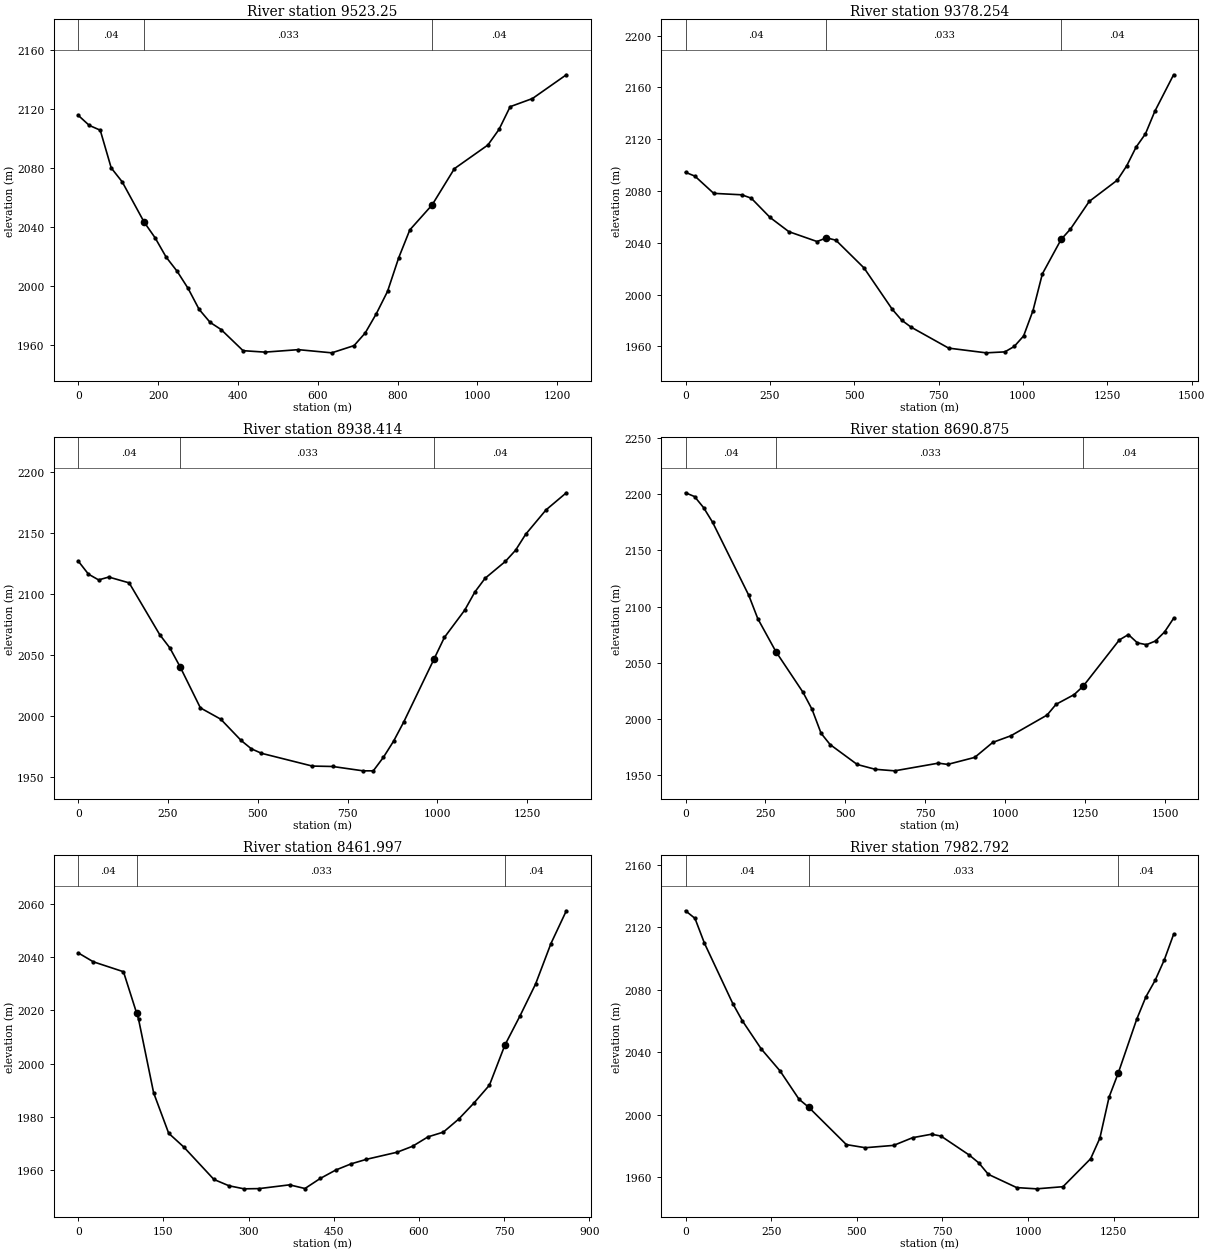
Type RM Length L Ch R = 1 ,9523.25 ,134.05,145,146.5
XS GIS Cut Line= 4
     481688.9545    3618704.7008     481197.2811    3618643.9279
     480549.1272    3618316.2916     480549.1272    3618315.2333
#Sta/Elev= 30
       0 2115.91   27.52 2109.11   55.05 2105.86   82.57 2080.29  110.09 2070.85
  165.14 2043.53  192.66 2032.88  220.18 2019.85  247.71 2010.26  275.23 1998.63
  302.75 1984.46  330.28 1975.65   357.8  1970.8  412.85 1956.47  467.89 1955.48
  551.28 1957.16  635.08    1955  690.95  1959.9  718.88 1968.45  746.81 1981.56
  774.74  1996.6  802.68 2019.34  830.61 2038.29  886.48 2055.22  942.34  2079.8
 1026.14 2095.79 1054.07 2106.37 1082.01 2121.78 1137.87  2127.3 1222.73  2143.4
#Mann= 3 , 0 , 0
       0     .04       0  165.14    .033       0  886.48     .04       0
Bank Sta=165.14,886.48
XS Rating Curve= 0 ,0
Exp/Cntr=0.3,0.1

Type RM Length L Ch R = 1 ,9378.254,308.66,439.84,414.22
XS GIS Cut Line= 3
     481989.5217    3618634.8506     481221.3478    3618500.9434
     480627.7968    3618197.4053
#Sta/Elev= 30
       0 2094.43   27.85 2091.49   83.55 2078.18  167.09 2077.05  194.94 2074.43
  250.64 2059.55  306.33 2048.58  389.88 2040.97  417.73 2043.83  445.58 2042.01
  529.12 2020.55  612.67 1988.64  640.52 1980.25  668.36 1974.87  779.76 1958.65
  890.87    1955  946.42 1955.74   974.2 1959.93 1001.98 1968.04 1029.76 1987.59
 1057.53 2015.97 1113.09 2042.56 1140.87 2050.62 1196.42 2071.94 1279.75 2088.39
 1307.53 2099.43 1335.31 2113.88 1363.09 2124.16 1390.86 2141.56 1446.42 2169.76
#Mann= 3 , 0 , 0
       0     .04       0  417.73    .033       0 1113.09     .04       0
Bank Sta=417.73,1113.09
XS Rating Curve= 0 ,0
Exp/Cntr=0.3,0.1

Type RM Length L Ch R = 1 ,8938.414,296.9,247.54,282.62
XS GIS Cut Line= 3
     482014.2162    3618560.7671     481499.2054    3618209.0506
     480846.5195    3617869.3213
#Sta/Elev= 30
       0  2127.2   28.35 2116.49    56.7 2111.76   85.04  2114.1  141.74 2109.33
  226.78 2066.87  255.13 2055.91  283.48 2040.53  340.17 2006.69  396.87 1997.41
  453.56 1979.96  481.91 1973.13  510.26 1969.41  651.95 1958.91  708.55 1958.58
  793.45    1955  821.75    1955  850.05 1966.16  878.35 1979.39  906.65 1995.15
  991.56 2047.15 1019.86 2064.56 1076.46 2086.94 1104.76 2101.86 1133.06 2113.05
 1189.66 2126.94 1217.96 2136.08 1246.26 2149.24 1302.86 2169.23 1359.46 2183.29
#Mann= 3 , 0 , 0
       0     .04       0  283.48    .033       0  991.56     .04       0
Bank Sta=283.48,991.56
XS Rating Curve= 0 ,0
Exp/Cntr=0.3,0.1

Type RM Length L Ch R = 1 ,8690.875,389.19,228.88,106.78
XS GIS Cut Line= 2
     482285.8557    3618380.8501     480945.2974    3617650.5986
#Sta/Elev= 30
       0 2201.11   28.27 2197.75   56.54 2187.94   84.81 2174.87  197.89 2110.02
  226.16 2089.24  282.69 2060.02   367.5 2023.88  395.77 2008.73  424.04 1987.46
  452.31 1977.44  537.12 1959.74  593.48 1955.47   654.1  1954.1  790.84 1960.93
  819.82 1959.81  904.62 1966.04  961.16 1979.39  1017.7 1985.25 1130.78 2003.63
 1159.05  2013.2 1215.59 2021.82 1243.86  2029.3 1356.94 2070.39 1385.21 2075.14
 1413.47 2067.78 1441.74 2066.15 1470.01 2069.46 1498.28 2077.44 1526.55 2089.55
#Mann= 3 , 0 , 0
       0     .04       0  282.69    .033       0 1243.86     .04       0
Bank Sta=282.69,1243.86
XS Rating Curve= 0 ,0
Exp/Cntr=0.3,0.1

Type RM Length L Ch R = 1 ,8461.997,400.78,479.21,347.18
XS GIS Cut Line= 3
     482003.6329    3617883.4324     481658.7866    3617873.6891
     481167.5479    3617721.1543
#Sta/Elev= 30
       0 2041.54   26.54  2038.2   79.61 2034.48  102.64 2019.04  106.15 2016.69
  132.69 1989.05  159.22 1973.86  185.76  1968.7  238.83 1956.53  265.37 1954.15
  291.91    1953  318.45 1953.09  372.06  1954.5  399.13 1953.12   426.2 1956.91
  453.27 1960.04  480.35 1962.37  507.42 1964.08  561.56 1966.75  588.64 1968.98
  615.71  1972.5  642.78 1974.28  669.85 1979.18  696.93 1985.26     724 1991.92
  751.07 2006.89  778.14 2018.05  805.21 2029.86  832.29 2045.07  859.36 2057.35
#Mann= 3 , 0 , 0
       0     .04       0  102.64    .033       0  751.07     .04       0
Bank Sta=102.64,751.07
XS Rating Curve= 0 ,0
Exp/Cntr=0.3,0.1

Type RM Length L Ch R = 1 ,7982.792,85.09,323.9,548.45
XS GIS Cut Line= 3
     482307.0224     3618021.016      481502.266    3617436.8264
     481072.2977    3617456.5705
#Sta/Elev= 30
       0 2130.56   27.62 2125.72   55.25 2109.84  138.12 2071.18  165.74 2060.27
  220.99 2042.24  276.23 2028.08  331.48 2010.02   359.1 2005.03   469.6 1981.02
  524.84 1979.03  607.71 1980.52  662.96 1985.44  718.21 1987.66  745.83 1986.48
   828.7 1974.28  856.32  1969.3  883.95 1962.02  966.82 1953.53 1024.85 1952.73
 1102.04  1954.1 1182.75 1971.99 1209.65 1985.13 1236.55 2011.39 1263.45 2026.84
 1317.26  2061.2 1344.16 2075.58 1371.06 2086.08 1397.96 2099.27 1424.86 2115.45
#Mann= 3 , 0 , 0
       0     .04       0   359.1    .033       0 1263.45     .04       0
Bank Sta=359.1,1263.45
XS Rating Curve= 0 ,0
Exp/Cntr=0.3,0.1

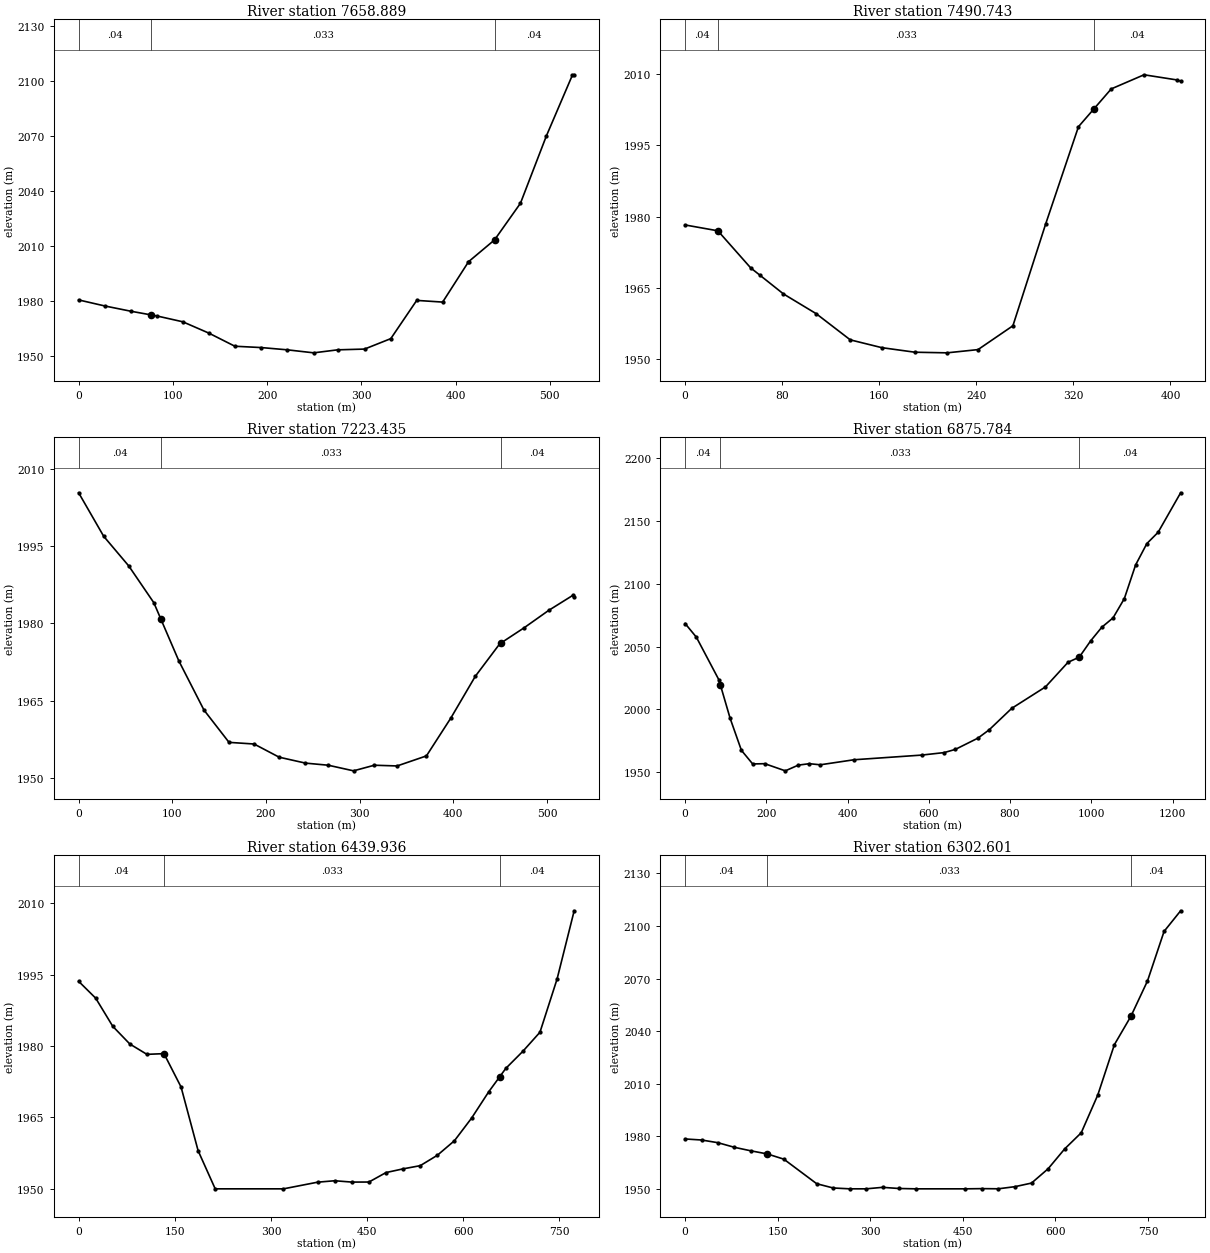
Type RM Length L Ch R = 1 ,7658.889,49.36,168.15,309.1
XS GIS Cut Line= 4
     481806.7825    3617636.4875     481751.2389    3617394.0143
     481645.9155    3617139.7754     481644.5044    3617141.1865
#Sta/Elev= 23
       0 1980.75   27.64 1977.47   55.28  1974.6      77 1972.57   82.92 1972.02
  110.56 1968.82   138.2 1962.65  165.84 1955.49  194.01 1954.76   221.5 1953.53
  249.52 1951.89  274.89 1953.53  303.44 1953.94  331.31 1959.64  358.83 1980.49
  386.35 1979.57  413.72 2001.49  413.87 2001.61  441.39 2013.47  468.91 2033.45
  496.43 2070.17  523.95 2103.23  525.94 2103.54
#Mann= 3 , 0 , 0
       0     .04       0      77    .033       0  441.39     .04       0
Bank Sta=77,441.39
XS Rating Curve= 0 ,0
Exp/Cntr=0.3,0.1

Type RM Length L Ch R = 1 ,7490.743,264.84,267.31,91.79
XS GIS Cut Line= 3
     481842.0603     3617654.832     481963.4161    3617268.1868
     481964.8273    3617265.3645
#Sta/Elev= 19
       0 1978.26   27.02 1977.03   54.03 1969.24   61.59 1967.71   81.05 1963.76
  108.06  1959.6  136.12  1954.1  162.11 1952.46  189.43  1951.5  215.86 1951.37
  241.41 1952.05  270.16 1957.06  297.18 1978.48  324.19 1998.92   336.6 2002.57
  351.21 2006.87  378.23 2009.84  405.24 2008.76   408.4 2008.51
#Mann= 3 , 0 , 0
       0     .04       0   27.02    .033       0   336.6     .04       0
Bank Sta=27.02,336.6
XS Rating Curve= 0 ,0
Exp/Cntr=0.3,0.1

Type RM Length L Ch R = 1 ,7223.435,620.03,347.65,120.8
XS GIS Cut Line= 4
     482059.3719    3617811.4656     482138.9626    3617584.2302
     482036.6177    3617316.1646     482037.1468    3617315.1063
#Sta/Elev= 24
       0 2005.37   26.75 1996.92    53.5 1991.16   80.26 1984.02   87.86  1980.8
  107.01  1972.7  133.76 1963.18  160.51  1956.9  187.27 1956.58  214.02 1954.02
  242.11 1952.87  266.43 1952.46  293.39 1951.37  315.59 1952.46  339.91 1952.32
   371.2 1954.27  397.28 1961.63  423.37 1969.73  449.45 1976.04  450.28 1976.14
  475.54 1979.16  501.62 1982.52  527.71 1985.48  528.89 1985.22
#Mann= 3 , 0 , 0
       0     .04       0   87.86    .033       0  450.28     .04       0
Bank Sta=87.86,450.28
XS Rating Curve= 0 ,0
Exp/Cntr=0.3,0.1

Type RM Length L Ch R = 1 ,6875.784,592.7,435.85,176.35
XS GIS Cut Line= 2
     482639.8689    3617737.7349     481657.3808     3617014.539
#Sta/Elev= 30
       0  2068.4   27.73 2057.52   83.18 2023.58   87.15 2019.19  110.91 1992.89
  138.63 1967.46  166.36 1956.62  196.12 1956.83   246.7 1951.14  278.77 1955.69
   305.9 1956.83  332.72 1955.95  415.89 1959.96  582.25 1963.67   637.7 1965.66
  665.43 1968.22  720.88 1977.17  748.61 1983.79  804.06 2000.86  887.24 2017.95
  942.69 2037.53  970.42 2041.63  998.15 2054.46 1025.87 2065.43  1053.6 2072.88
 1081.33  2088.2 1109.05 2114.97 1136.78 2132.01  1164.5 2140.99 1219.96 2172.44
#Mann= 3 , 0 , 0
       0     .04       0   87.15    .033       0  970.42     .04       0
Bank Sta=87.15,970.42
XS Rating Curve= 0 ,0
Exp/Cntr=0.3,0.1

Type RM Length L Ch R = 1 ,6439.936,149.76,137.34,155.83
XS GIS Cut Line= 3
     482680.4384    3617123.9004     482302.9654    3617254.4284
     481934.3119    3617194.4561
#Sta/Elev= 27
       0 1993.61   26.63 1990.06   53.25 1984.15   79.88 1980.43  106.51 1978.26
  133.13 1978.41  159.76  1971.4  186.39    1958  213.02    1950  319.52    1950
  372.78  1951.4   399.4  1951.7  426.08 1951.42  452.76 1951.43  479.44 1953.42
  506.12  1954.2   532.8 1954.87  559.48 1957.05  586.15 1960.11  612.83 1964.85
  639.51 1970.37  656.68 1973.54  666.19  1975.3  692.87  1978.9  719.55 1982.91
  746.22 1994.08   772.9 2008.43
#Mann= 3 , 0 , 0
       0     .04       0  133.13    .033       0  656.68     .04       0
Bank Sta=133.13,656.68
XS Rating Curve= 0 ,0
Exp/Cntr=0.3,0.1

Type RM Length L Ch R = 1 ,6302.601,218.67,312.19,201.5
XS GIS Cut Line= 3
     482537.5631    3617053.3447      482211.243    3617170.1143
     481777.3255    3617028.6502
#Sta/Elev= 28
       0 1978.46   26.66 1977.87   53.32 1976.32   79.98 1973.69  106.64 1971.69
   133.3 1969.91  159.96 1966.94  213.28 1952.91  239.94 1950.49   266.6 1950.01
  293.26    1950  319.92 1950.85  346.58  1950.2  373.43    1950  453.97    1950
  480.82 1950.12  507.66 1950.03  534.51 1951.24  561.36 1953.29   588.2 1961.44
  615.05 1972.78   641.9 1981.99  668.74 2003.56  695.59 2032.26  722.44  2048.5
  749.28 2068.65  776.13 2096.91  802.98 2108.68
#Mann= 3 , 0 , 0
       0     .04       0   133.3    .033       0  722.44     .04       0
Bank Sta=133.3,722.44
XS Rating Curve= 0 ,0
Exp/Cntr=0.3,0.1

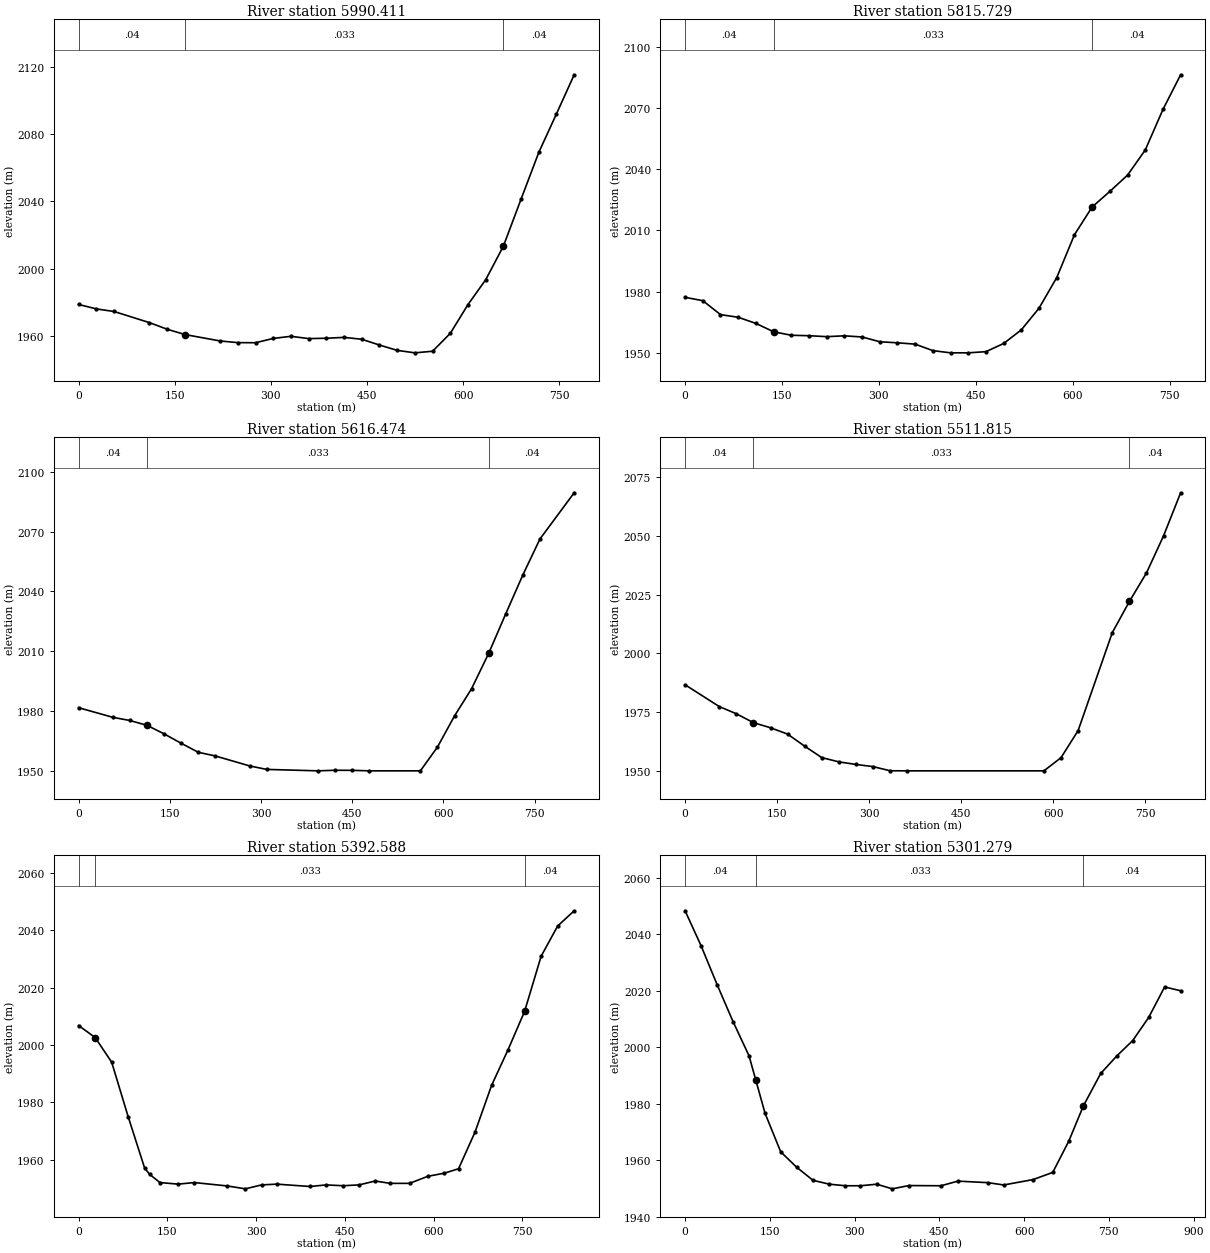
Type RM Length L Ch R = 1 ,5990.411,147.72,174.68,216.72
XS GIS Cut Line= 2
     482560.4937    3616984.5529     481798.4922    3616852.2609
#Sta/Elev= 27
       0 1978.72   27.62 1976.09   55.24 1974.55  110.49 1967.95  138.11 1964.02
  165.73 1960.88  220.97 1957.04  248.59 1956.06  276.21    1956  303.84 1958.57
  331.46 1959.82  359.08 1958.45   386.7 1958.67  414.32 1959.18  441.94 1958.06
  469.56 1954.63  497.19 1951.46  524.81    1950  552.43 1950.95  580.05 1961.57
  607.67 1978.66  635.29 1993.39  662.91 2013.33  690.54 2041.28  718.16    2069
  745.78 2091.92   773.4 2115.11
#Mann= 3 , 0 , 0
       0     .04       0  165.73    .033       0  662.91     .04       0
Bank Sta=165.73,662.91
XS Rating Curve= 0 ,0
Exp/Cntr=0.3,0.1

Type RM Length L Ch R = 1 ,5815.729,204.87,199.26,223.13
XS GIS Cut Line= 2
     482567.5493    3616912.2333     481858.4645    3616619.4271
#Sta/Elev= 29
       0  1977.2    27.4 1975.56    54.8 1968.73    82.2 1967.43  109.59 1964.42
  136.99 1960.33  164.39 1958.61  191.79 1958.39  219.19 1957.93  246.59 1958.34
  273.99 1957.77  301.38 1955.43  328.78 1954.91  356.18 1954.26  383.58 1951.08
  410.98    1950  438.38    1950  465.78 1950.58  493.18 1954.59  520.57 1961.28
  547.97  1971.9  575.37 1986.89  602.77 2007.86  630.17 2021.48  657.57 2029.11
  684.97 2037.08  712.36 2049.38  739.76 2069.24  767.16 2086.25
#Mann= 3 , 0 , 0
       0     .04       0  136.99    .033       0  630.17     .04       0
Bank Sta=136.99,630.17
XS Rating Curve= 0 ,0
Exp/Cntr=0.3,0.1

Type RM Length L Ch R = 1 ,5616.474,98.43,104.66,100.69
XS GIS Cut Line= 2
     482742.1746    3616811.6914     482010.1593    3616453.6212
#Sta/Elev= 23
       0 1981.68    56.2 1976.85    84.3 1975.26   112.4 1972.84   140.5 1968.56
   168.6 1963.84   196.7 1959.32   224.8 1957.46     281 1952.49   309.1 1950.72
   393.4    1950   421.5 1950.28   449.6 1950.25   477.7    1950     562    1950
   590.1 1961.93   618.2 1977.59   646.3 1991.28   674.4 2009.01   702.5 2028.87
   730.6 2048.36   758.7 2066.37   814.9 2089.52
#Mann= 3 , 0 , 0
       0     .04       0   112.4    .033       0   674.4     .04       0
Bank Sta=112.4,674.4
XS Rating Curve= 0 ,0
Exp/Cntr=0.3,0.1

Type RM Length L Ch R = 1 ,5511.815,133.73,119.23,110.55
XS GIS Cut Line= 2
     482810.9664    3616749.9552     482091.2983    3616383.0656
#Sta/Elev= 21
       0 1986.65   55.71 1977.37   83.56  1974.3  111.42 1970.51  139.27 1968.34
  167.13 1965.64  194.98 1960.49  222.84 1955.63  250.69 1953.82  278.55 1952.72
   306.4  1951.8  334.26 1950.03  362.11    1950  584.95    1950  612.81 1955.61
  640.66 1967.14  696.37 2008.85  724.23 2022.12  752.08 2034.26  779.94 2050.07
  807.79 2068.41
#Mann= 3 , 0 , 0
       0     .04       0  111.42    .033       0  724.23     .04       0
Bank Sta=111.42,724.23
XS Rating Curve= 0 ,0
Exp/Cntr=0.3,0.1

Type RM Length L Ch R = 1 ,5392.588,111.36,91.31,78.31
XS GIS Cut Line= 2
     482890.3416    3616665.2883     482142.4512    3616287.8154
#Sta/Elev= 30
       0 2006.81   27.93 2002.61   55.85 1994.03   83.78 1974.98   111.7 1957.01
  120.23 1954.87  137.44 1952.03  168.28 1951.48  195.59 1952.03  251.33 1950.85
  281.94 1949.84  309.25 1951.21   334.8 1951.48  391.19 1950.66   418.5 1951.21
   446.7 1950.93  474.01 1951.21  501.32 1952.57  526.87 1951.75  559.47 1951.75
  590.31 1954.21   618.5 1955.31  642.28 1956.85   670.2 1969.66  698.13 1985.92
  726.05  1998.4  753.98 2011.77   781.9 2030.99  809.83 2041.52  837.75 2046.83
#Mann= 3 , 0 , 0
       0     .04       0   27.93    .033       0  753.98     .04       0
Bank Sta=27.93,753.98
XS Rating Curve= 0 ,0
Exp/Cntr=0.3,0.1

Type RM Length L Ch R = 1 ,5301.279,134.09,113.07,91.92
XS GIS Cut Line= 2
     482971.4807    3616585.9132     482174.2013    3616220.7874
#Sta/Elev= 30
       0 2048.26   28.29 2035.88   56.57 2022.15   84.86 2009.03  113.15 1996.91
  124.83 1988.53  141.44  1976.6  169.16 1962.96  197.36 1957.49  226.43 1952.85
  255.51 1951.48   283.7 1950.93  310.13 1950.93  339.21 1951.48  366.52 1949.84
  396.02    1951  452.86 1950.93  482.82 1952.57  535.68 1952.03  563.88 1951.21
  615.86 1953.12  650.61 1955.66   678.9 1966.69  704.88 1979.23  735.47 1990.67
  763.76 1996.85  792.05  2002.3  820.34  2010.5  848.62  2021.3  876.91 2019.95
#Mann= 3 , 0 , 0
       0     .04       0  124.83    .033       0  704.88     .04       0
Bank Sta=124.83,704.88
XS Rating Curve= 0 ,0
Exp/Cntr=0.3,0.1

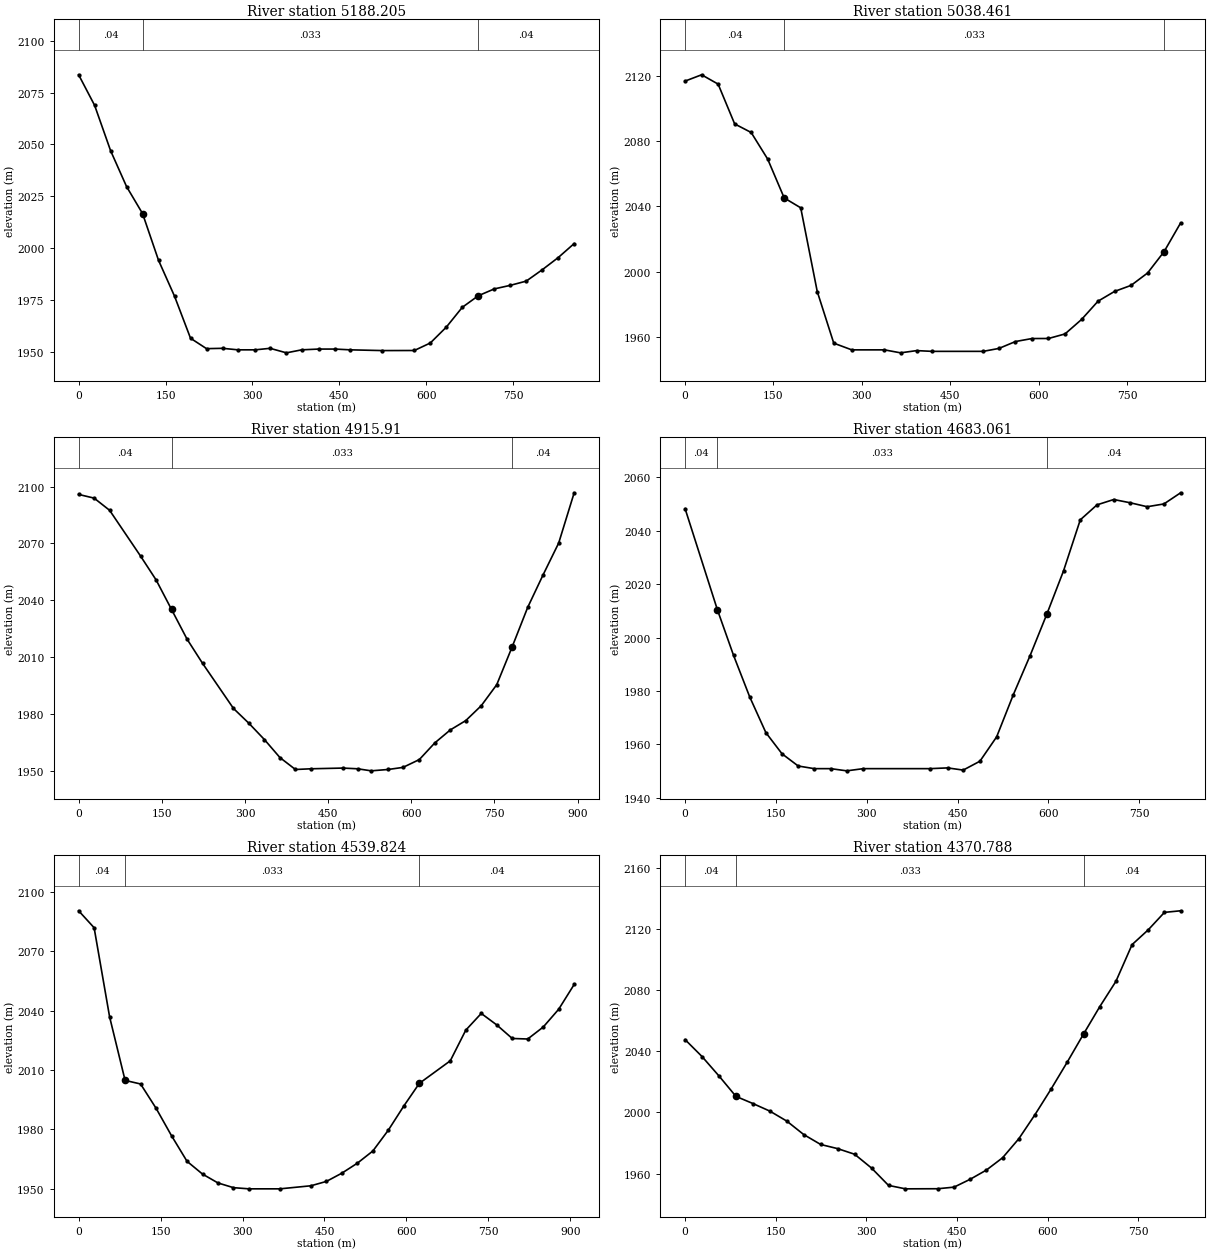
Type RM Length L Ch R = 1 ,5188.205,240.43,149.74,88.44
XS GIS Cut Line= 2
     483004.9946    3616455.3851     482209.4791    3616141.4123
#Sta/Elev= 30
       0  2083.6   27.59 2068.85   55.18 2046.97   82.76 2029.65  110.35 2016.64
  137.94 1994.08  165.53 1976.78  193.12 1956.52  220.71  1951.5  248.46 1951.66
  274.89 1950.93  304.85 1950.93   330.4 1951.66  358.59 1949.48  385.02 1950.93
   414.1  1951.3  442.29  1951.3  468.72 1950.93  524.23 1950.57  579.35 1950.61
  606.94 1954.23  634.53 1961.87  662.12 1971.43   689.7 1977.01  717.29 1980.31
  744.88 1982.03  772.47 1984.07  800.06 1989.54  827.64 1995.42  855.23 2002.19
#Mann= 3 , 0 , 0
       0     .04       0  110.35    .033       0   689.7     .04       0
Bank Sta=110.35,689.7
XS Rating Curve= 0 ,0
Exp/Cntr=0.3,0.1

Type RM Length L Ch R = 1 ,5038.461,140.1,122.55,108.91
XS GIS Cut Line= 2
     483050.8558    3616231.3708     482225.3542    3616070.8566
#Sta/Elev= 28
       0 2117.09   28.03 2120.97   56.06 2115.23    84.1 2090.77  112.13 2085.49
  140.16 2069.13  168.19 2045.25  196.22 2039.18  224.26 1987.71  252.29 1955.97
  282.82 1951.85  338.33 1951.85  365.64 1950.02  392.95 1951.39  419.38 1950.93
  505.73 1950.93  532.61 1952.73  560.64 1956.97  588.67 1958.81  616.71 1958.84
  644.74 1961.64  672.77 1970.52   700.8 1981.78  728.83 1987.78  756.87  1991.5
   784.9 1999.12  812.93 2012.27  840.96  2029.9
#Mann= 3 , 0 , 0
       0     .04       0  168.19    .033       0  812.93     .04       0
Bank Sta=168.19,812.93
XS Rating Curve= 0 ,0
Exp/Cntr=0.3,0.1

Type RM Length L Ch R = 1 ,4915.91 ,70.17,232.85,215.64
XS GIS Cut Line= 2
     483091.4253    3616088.4955     482205.9513    3615966.7869
#Sta/Elev= 30
       0 2095.82   27.93 2093.87   55.86 2087.44  111.72 2063.25  139.66  2050.7
  167.59 2035.06  195.52 2019.41  223.45 2006.64  279.31 1982.78  307.24 1974.92
  335.17 1966.33  363.11 1956.84  391.04 1950.55  419.38 1950.93  476.65  1951.3
  503.08 1950.93  527.75 1949.84  558.59 1950.57  585.02 1951.66  614.49 1955.79
  642.42 1964.59  670.35 1971.44  698.28 1976.38  726.21 1984.24  754.14 1995.34
  782.07 2015.41  810.01 2036.19  837.94 2053.47  865.87 2070.15   893.8 2096.69
#Mann= 3 , 0 , 0
       0     .04       0  167.59    .033       0  782.07     .04       0
Bank Sta=167.59,782.07
XS Rating Curve= 0 ,0
Exp/Cntr=0.3,0.1

Type RM Length L Ch R = 1 ,4683.061,212.84,143.24,154.33
XS GIS Cut Line= 3
     482987.3557    3616046.1621      482752.758    3615869.7729
     482239.4653    3615760.4115
#Sta/Elev= 27
       0 2048.21   53.37 2010.36   80.05  1993.3  106.73 1977.76  133.41  1964.4
   160.1 1956.48  186.78 1951.92  213.22 1950.93  240.53 1950.93  266.96 1950.11
  294.27 1950.93  404.41 1950.93  433.48 1951.21  459.24 1950.39  486.86 1953.71
  514.49 1962.83  542.11 1978.65  569.73 1993.24  597.35 2008.74  624.97 2024.96
  652.59 2044.03  680.22 2049.64  707.84 2051.64  735.46  2050.4  763.08 2048.94
   790.7 2049.98  818.33 2054.16
#Mann= 3 , 0 , 0
       0     .04       0   53.37    .033       0  597.35     .04       0
Bank Sta=53.37,597.35
XS Rating Curve= 0 ,0
Exp/Cntr=0.3,0.1

Type RM Length L Ch R = 1 ,4539.824,240.6,169.04,202.37
XS GIS Cut Line= 2
     483191.9672    3615885.6479     482315.3127    3615652.8141
#Sta/Elev= 30
       0 2090.54   28.35 2081.97   56.69 2036.92   85.04 2004.81  113.38    2003
  141.73 1990.73  170.07 1976.83  198.42 1963.91  226.76 1957.46  255.11 1952.97
  283.45 1950.59   311.8    1950  368.49    1950  425.18 1951.55  453.52 1953.75
  481.87 1957.93  510.21 1962.97  538.56 1969.13   566.9 1979.67  595.25 1991.88
  623.59  2003.3  680.29 2014.71  708.63  2030.2  736.98 2038.65  765.32 2032.85
  793.67    2026  822.01 2025.73  850.36 2031.77   878.7 2040.77  907.05  2053.3
#Mann= 3 , 0 , 0
       0     .04       0   85.04    .033       0  623.59     .04       0
Bank Sta=85.04,623.59
XS Rating Curve= 0 ,0
Exp/Cntr=0.3,0.1

Type RM Length L Ch R = 1 ,4370.788,140.17,159.51,113.42
XS GIS Cut Line= 3
       483211.37    3615615.7724     482847.3026    3615636.4099
     482403.5073    3615534.6333
#Sta/Elev= 30
       0 2047.56   28.05 2036.49    56.1 2023.79   84.15 2010.45   112.2 2005.78
  140.25 2000.82   168.3 1994.29  196.35 1985.48   224.4    1979  252.45 1976.29
   280.5 1972.62  308.55 1963.57   336.6 1952.25  364.65    1950  418.22 1950.07
     445 1951.11  471.79 1956.27  498.57 1962.28  525.35 1970.32  552.13 1982.71
  578.92 1998.48   605.7 2015.31  632.48 2032.96  659.27  2051.2  686.05 2069.05
  712.83 2085.63  739.62 2109.68   766.4 2119.37  793.18 2130.77  819.97 2131.81
#Mann= 3 , 0 , 0
       0     .04       0   84.15    .033       0  659.27     .04       0
Bank Sta=84.15,659.27
XS Rating Curve= 0 ,0
Exp/Cntr=0.3,0.1

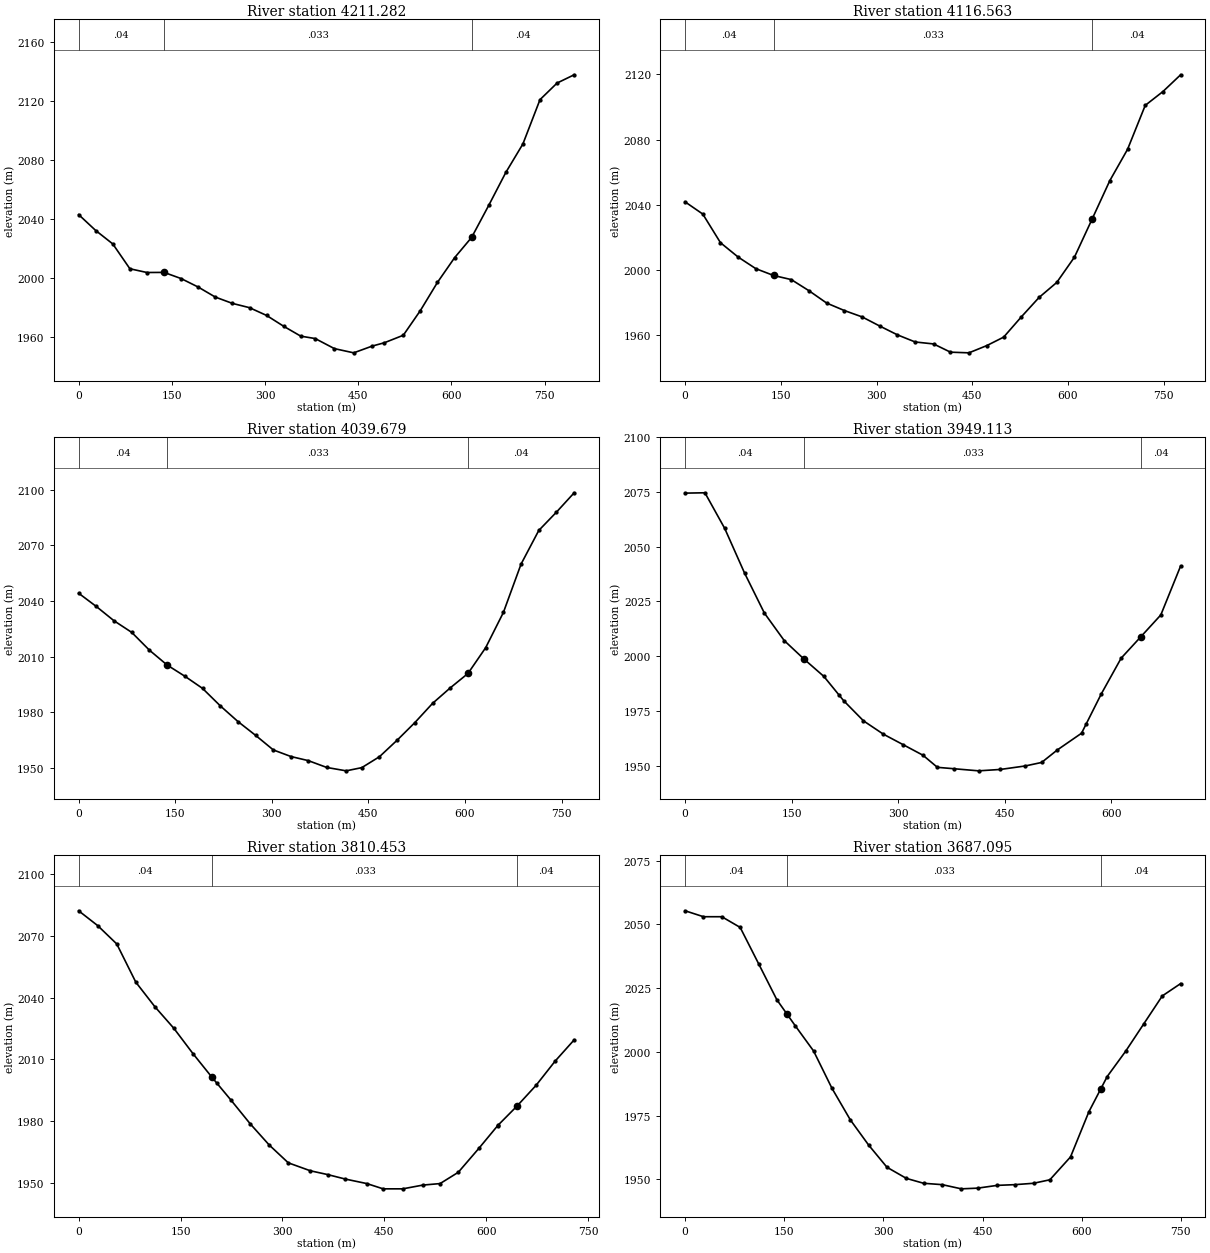
Type RM Length L Ch R = 1 ,4211.282,92.44,94.72,96.23
XS GIS Cut Line= 2
     483223.7173    3615492.2999     482426.4379    3615478.1887
#Sta/Elev= 30
       0 2043.22    27.5 2032.44   54.99 2023.33   82.49 2006.51  109.99 2003.98
  137.48 2004.05  164.98 1999.86  192.48  1994.1  219.97 1987.32  247.47 1983.05
  274.97 1980.14  302.46 1974.88  329.96 1967.54  357.46 1960.84  380.62 1959.23
  411.63 1952.39  442.64 1949.54  472.25  1954.1  491.98 1956.38  522.44 1961.46
  549.93  1978.2  577.43  1997.3  604.93 2013.98  632.42 2027.78  659.92 2049.47
  687.42 2071.79  714.91  2091.1  742.41 2121.12  769.91 2132.37   797.4 2137.97
#Mann= 3 , 0 , 0
       0     .04       0  137.48    .033       0  632.42     .04       0
Bank Sta=137.48,632.42
XS Rating Curve= 0 ,0
Exp/Cntr=0.3,0.1

Type RM Length L Ch R = 1 ,4116.563,64.59,76.88,85.17
XS GIS Cut Line= 2
     483197.2589    3615404.1053     482421.1462    3615379.4108
#Sta/Elev= 29
       0 2041.71   27.73 2034.22   55.46 2016.62    83.2  2007.8  110.93 2000.68
  138.66 1996.52  166.39 1993.99  194.13 1987.15  221.86 1979.57  249.59 1974.99
  277.32 1971.09  305.06 1965.46  332.79 1960.05  360.52 1955.69  389.39 1954.48
  415.86 1949.43  444.76 1949.02  472.65 1953.45  499.18 1958.67  526.91 1971.11
  554.65 1983.02  582.38 1992.23  610.11 2007.77  637.84 2031.18  665.58 2054.78
  693.31 2073.95  721.04 2100.96  748.77 2109.44  776.51 2119.74
#Mann= 3 , 0 , 0
       0     .04       0  138.66    .033       0  637.84     .04       0
Bank Sta=138.66,637.84
XS Rating Curve= 0 ,0
Exp/Cntr=0.3,0.1

Type RM Length L Ch R = 1 ,4039.679,76.53,90.57,101.11
XS GIS Cut Line= 2
       483179.62    3615345.8968     482412.3268    3615285.9245
#Sta/Elev= 29
       0  2044.2   27.49 2037.03   54.97 2029.32   82.46 2023.05  109.95 2013.44
  137.43 2005.43  164.92 1999.38  192.41 1992.81   219.9 1983.41  247.38 1974.92
  274.87 1967.44  302.36 1959.57  329.84    1956  356.73 1953.79  385.31 1950.11
  415.51 1948.28  439.79 1950.01  467.28 1955.92  494.76 1964.86  522.25 1974.35
  549.74 1984.73  577.23  1993.1  604.71 2000.87   632.2  2014.8  659.69 2033.81
  687.17 2059.95  714.66 2078.09  742.15    2088  769.63 2098.44
#Mann= 3 , 0 , 0
       0     .04       0  137.43    .033       0  604.71     .04       0
Bank Sta=137.43,604.71
XS Rating Curve= 0 ,0
Exp/Cntr=0.3,0.1

Type RM Length L Ch R = 1 ,3949.113,102.69,138.66,169.18
XS GIS Cut Line= 2
     483184.9116    3615280.6328     482493.4658    3615187.1465
#Sta/Elev= 28
       0 2074.45   27.91 2074.61   55.82 2058.31   83.73 2037.95  111.64 2019.68
  139.55 2007.14  167.46 1998.67  195.37 1990.77  216.97 1982.18  223.28 1979.67
  251.19 1970.47  279.09 1964.41     307  1959.6  334.91 1954.78  355.24 1949.25
  378.68 1948.61  413.22 1947.65  444.05 1948.29  479.21 1949.89  502.03 1951.48
  524.23 1957.22  558.19 1964.82  564.99 1969.21   586.1 1982.83  614.01 1999.11
  641.92 2008.95  669.83 2018.83  697.74 2041.19
#Mann= 3 , 0 , 0
       0     .04       0  167.46    .033       0  641.92     .04       0
Bank Sta=167.46,641.92
XS Rating Curve= 0 ,0
Exp/Cntr=0.3,0.1

Type RM Length L Ch R = 1 ,3810.453,86.18,123.36,157.84
XS GIS Cut Line= 2
     483220.1895    3615217.1327     482519.9242    3615012.5211
#Sta/Elev= 29
       0 2082.06   28.06 2074.87   56.12 2065.99   84.18 2047.46  112.24 2035.56
   140.3 2025.05  168.36 2012.81  196.42 2001.31  203.53  1998.5  224.48 1990.22
  252.54 1978.83  280.59 1968.53  308.65  1959.9  341.15 1956.04  366.52 1954.21
   392.6 1952.03  424.32 1949.84  448.28 1947.29  477.18 1947.29  506.78 1949.11
  532.16 1949.84  558.94 1955.31  589.25 1966.91  617.01 1977.95  617.31 1978.07
  645.37  1987.4  673.43 1997.45  701.49 2009.18  729.55  2019.5
#Mann= 3 , 0 , 0
       0     .04       0  196.42    .033       0  645.37     .04       0
Bank Sta=196.42,645.37
XS Rating Curve= 0 ,0
Exp/Cntr=0.3,0.1

Type RM Length L Ch R = 1 ,3687.095,117.85,122.7,132.05
XS GIS Cut Line= 2
     483250.1757    3615167.7437     482569.3132    3614853.7708
#Sta/Elev= 30
       0 2055.33   27.77    2053   55.54    2053   83.31 2048.81  111.08 2034.64
  138.85 2020.43  153.73 2014.98  166.62 2010.25  194.38 2000.36  222.15 1985.75
  249.92 1973.37  277.69 1963.46  305.46 1954.75   334.8 1950.39  360.88 1948.47
  389.07 1947.93  417.97 1946.29  442.64 1946.56  472.25 1947.65  499.03 1947.93
  527.22 1948.47  551.89 1949.84  583.15  1958.8  610.92  1976.5  629.06 1985.54
  638.69 1990.34  666.46 2000.21  694.23 2011.08     722 2021.94  749.77 2026.78
#Mann= 3 , 0 , 0
       0     .04       0  153.73    .033       0  629.06     .04       0
Bank Sta=153.73,629.06
XS Rating Curve= 0 ,0
Exp/Cntr=0.3,0.1