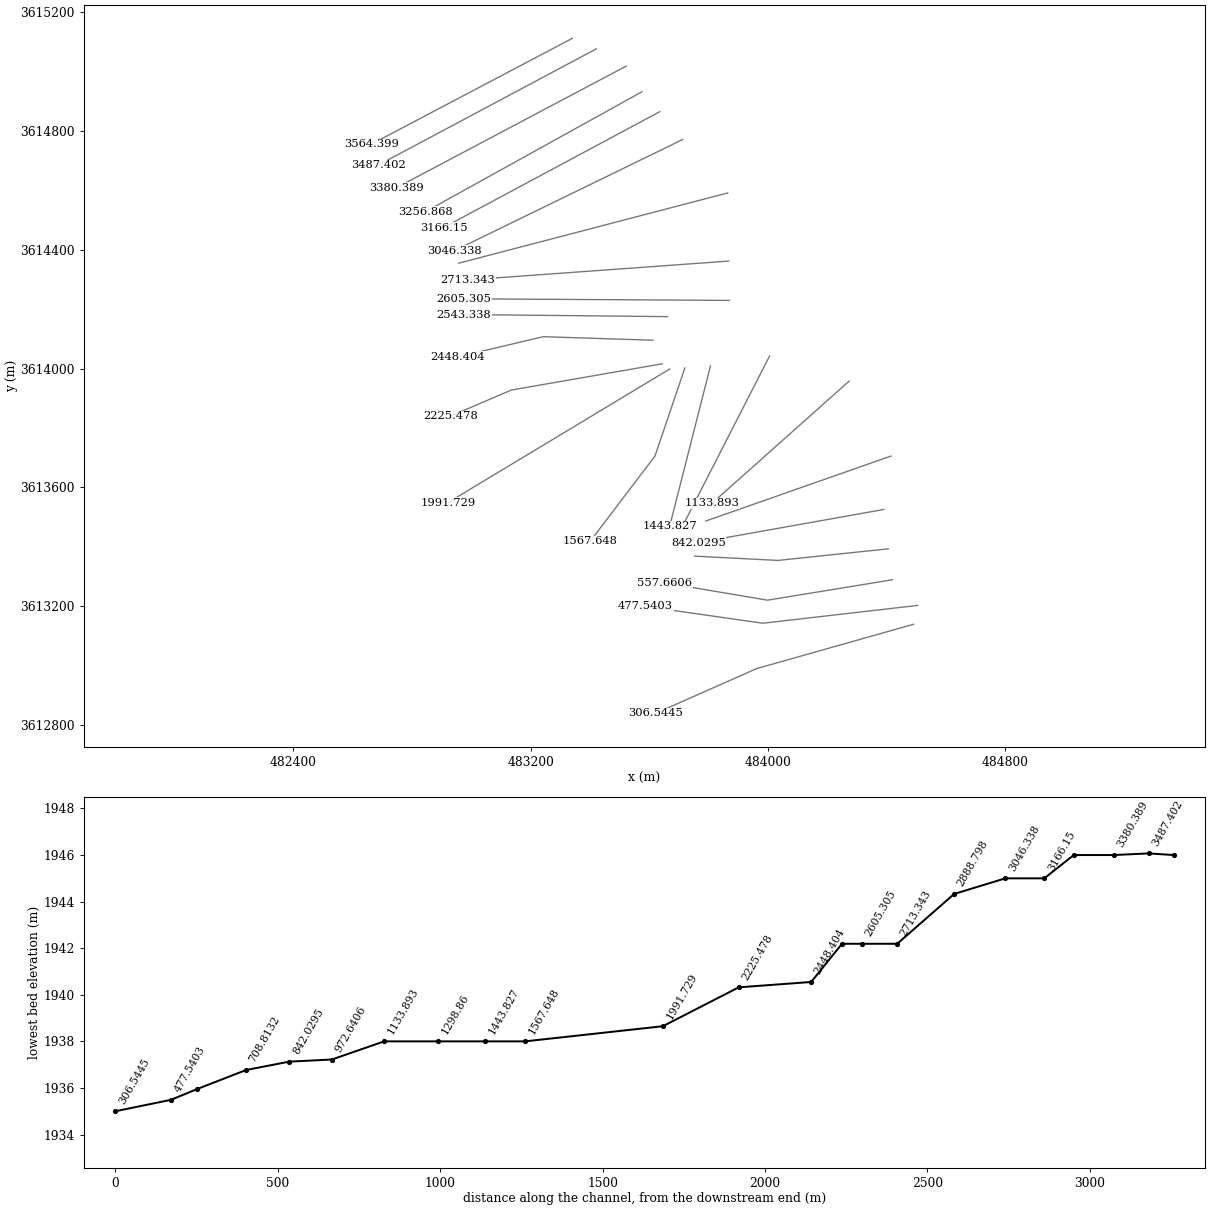
HEC-RAS study Flood.prj: Flood

--- Flood.g01 (geometry) --- (continued)

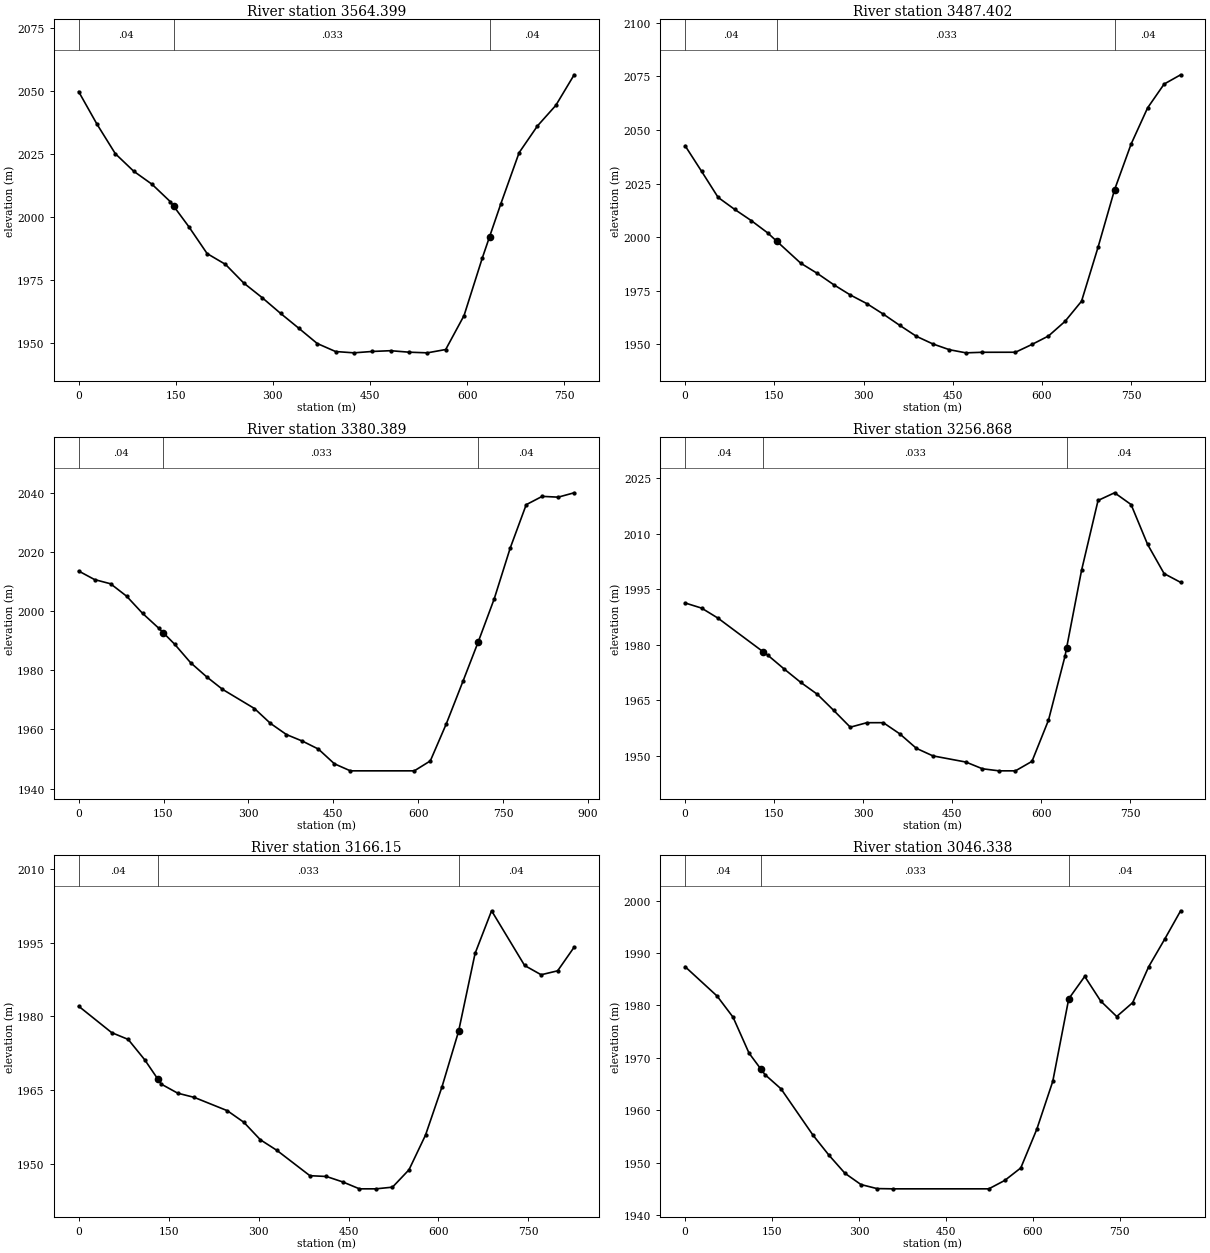
Type RM Length L Ch R = 1 ,3564.399,80.51,77,77.09
XS GIS Cut Line= 2
     483340.1342    3615111.2991     482662.7995    3614754.9929
#Sta/Elev= 30
       0 2049.82   28.35 2036.86   56.69 2025.13   85.04 2018.18  113.38 2012.98
  141.73 2006.04  146.76 2004.29  170.07 1996.17  198.42 1985.45  226.77 1981.16
  255.11 1973.72  283.46 1967.93   311.8  1961.7  340.15 1955.75  368.49 1949.71
  396.84 1946.52  425.19    1946  453.53 1946.55  481.88 1946.85  510.22 1946.26
  538.57    1946  566.91 1947.32  595.26 1960.82  623.61 1983.82  634.64 1992.12
  651.95 2005.15   680.3 2025.55  708.64 2036.18  736.99 2044.34  765.33  2056.5
#Mann= 3 , 0 , 0
       0     .04       0  146.76    .033       0  634.64     .04       0
Bank Sta=146.76,634.64
XS Rating Curve= 0 ,0
Exp/Cntr=0.3,0.1

Type RM Length L Ch R = 1 ,3487.402,107.55,107.01,108.2
XS GIS Cut Line= 2
     483421.2732    3615076.0213     482685.7301    3614684.4372
#Sta/Elev= 30
       0 2042.66   27.78 2030.69   55.55 2018.55   83.33 2012.97   111.1 2007.77
  138.88    2002  154.06 1998.13  194.43 1987.88  222.21 1983.14  249.99 1977.83
  277.76 1973.07  305.54 1969.03  333.31 1964.12  361.09 1958.86  388.87 1953.79
  416.64 1950.22  444.42 1947.53  472.19 1946.07  499.97 1946.33  555.52 1946.35
   583.3 1949.99  611.07 1953.93  638.85 1960.74  666.63 1970.14   694.4 1995.32
  722.18 2022.14  749.96 2043.41  777.73 2060.31  805.51 2071.41  833.28 2075.74
#Mann= 3 , 0 , 0
       0     .04       0  154.06    .033       0  722.18     .04       0
Bank Sta=154.06,722.18
XS Rating Curve= 0 ,0
Exp/Cntr=0.3,0.1

Type RM Length L Ch R = 1 ,3380.389,109.04,123.52,130.08
XS GIS Cut Line= 2
     483521.8151    3615017.8128     482747.4663    3614608.5898
#Sta/Elev= 29
       0 2013.51   28.25 2010.61   56.51 2009.19   84.76 2005.01  113.01  1999.2
  141.26 1994.25  149.93 1992.59  169.52 1988.82  197.77 1982.56  226.02  1977.8
  254.27 1973.54  310.78 1967.05  339.03 1962.03  367.28 1958.26  395.54 1956.04
  423.79 1953.35  452.04 1948.38  480.29    1946   593.3    1946  621.56 1949.35
  649.81 1961.88  679.66 1976.45  706.31  1989.6  734.57 2004.13  762.82 2021.29
  791.07 2035.92  819.33 2038.73  847.58 2038.46  875.83 2039.94
#Mann= 3 , 0 , 0
       0     .04       0  149.93    .033       0  706.31     .04       0
Bank Sta=149.93,706.31
XS Rating Curve= 0 ,0
Exp/Cntr=0.3,0.1

Type RM Length L Ch R = 1 ,3256.868,92.04,90.72,86.28
XS GIS Cut Line= 2
     483574.7319    3614931.3821     482844.4804    3614527.4507
#Sta/Elev= 30
       0 1991.31   27.82 1989.92   55.63 1987.19   131.2 1978.16  139.09 1977.24
   166.9 1973.48  194.72 1969.88  222.54 1966.68  250.36  1962.3  278.17 1957.78
  305.99 1958.99  333.81    1959  361.63 1955.97  389.44 1952.08  417.26 1950.04
   472.9 1948.37  500.71 1946.56  528.53    1946  556.35    1946  584.17 1948.56
  611.98 1959.68   639.8 1976.96  642.37  1979.1  667.62 2000.09  695.44 2018.98
  723.25 2021.05  751.07 2017.87  778.89 2007.11   806.7 1999.23  834.52 1996.87
#Mann= 3 , 0 , 0
       0     .04       0   131.2    .033       0  642.37     .04       0
Bank Sta=131.2,642.37
XS Rating Curve= 0 ,0
Exp/Cntr=0.3,0.1

Type RM Length L Ch R = 1 ,3166.15 ,116,119.81,95.58
XS GIS Cut Line= 2
     483634.7042    3614864.3542     482906.2166     3614474.534
#Sta/Elev= 28
       0 1982.09   55.08 1976.72   82.62 1975.34  110.16 1971.21  132.27 1967.25
   137.7 1966.27  165.25 1964.42  192.79 1963.57  247.87 1960.87  275.41 1958.52
  302.95 1954.97  330.49 1952.82  385.57 1947.67  413.11 1947.51  440.66 1946.39
   468.2    1945  495.74    1945  523.28 1945.34  550.82 1948.87  578.36 1955.91
   605.9 1965.73  633.44 1976.95  660.98 1992.79  688.52 2001.46  743.61 1990.35
  771.15 1988.47  798.69 1989.27  826.23 1994.08
#Mann= 3 , 0 , 0
       0     .04       0  132.27    .033       0  633.44     .04       0
Bank Sta=132.27,633.44
XS Rating Curve= 0 ,0
Exp/Cntr=0.3,0.1

Type RM Length L Ch R = 1 ,3046.338,196.25,157.54,79.2
XS GIS Cut Line= 2
     483712.3155    3614770.8679     482943.2584    3614396.9227
#Sta/Elev= 26
       0  1987.4   55.17  1981.8   82.76 1977.76  110.34  1970.9  130.67 1967.87
  137.93 1966.79  165.51 1964.09  220.68 1955.25  248.27 1951.42  275.86 1947.97
  303.44 1945.82  331.03 1945.05  358.61    1945  524.12    1945  551.71 1946.61
   579.3 1948.99  606.88 1956.36  634.47 1965.51  662.05 1981.27  689.64 1985.54
  717.22 1980.84  744.81 1977.89  772.39 1980.54  799.98 1987.39  827.57 1992.64
  855.15 1998.07
#Mann= 3 , 0 , 0
       0     .04       0  130.67    .033       0  662.05     .04       0
Bank Sta=130.67,662.05
XS Rating Curve= 0 ,0
Exp/Cntr=0.3,0.1

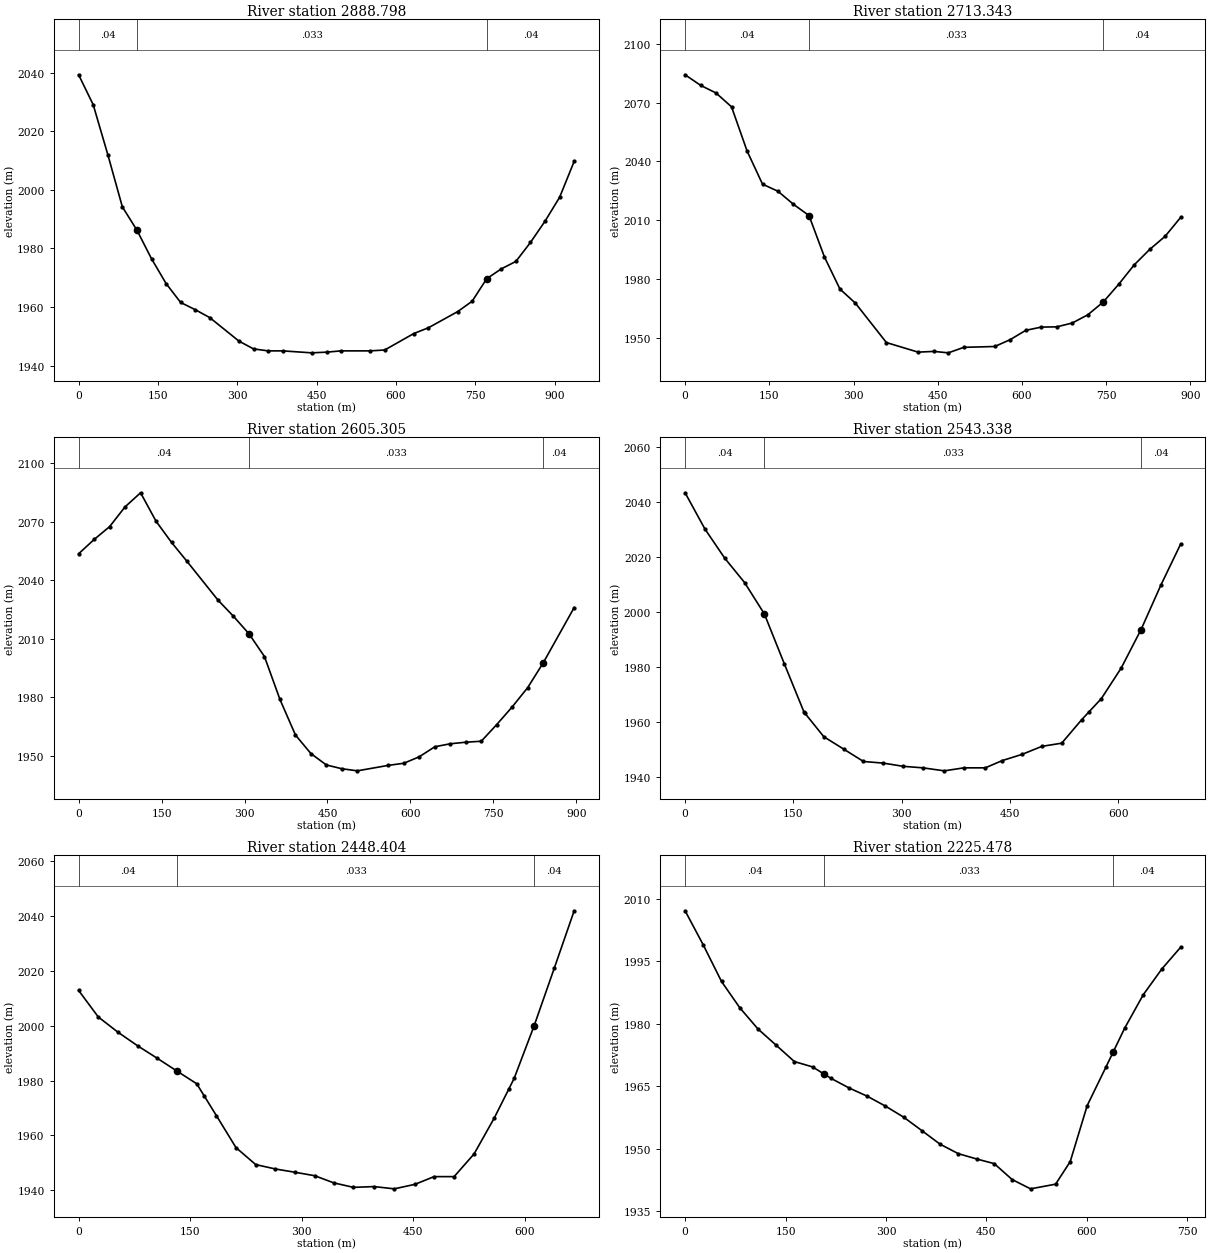
Type RM Length L Ch R = 1 ,2888.798,206.87,175.45,98.21
XS GIS Cut Line= 2
     483864.0102    3614590.9509     482957.3695    3614354.5893
#Sta/Elev= 30
       0 2039.27   27.56 2029.04   55.11 2012.05   82.67 1994.17  110.23 1986.21
  137.79 1976.46  165.34    1968   192.9 1961.52  220.46 1959.07  248.01 1956.35
  303.13 1948.33  330.69 1945.68  358.24    1945   385.8    1945  440.53 1944.33
  468.72 1944.56  496.03    1945  551.14    1945   578.7  1945.3  633.82 1950.93
  661.37 1952.89  716.49 1958.39  744.04 1961.95   771.6 1969.65  799.16    1973
  826.72 1975.54  854.27 1982.01  881.83 1989.28  909.39 1997.43  936.94  2009.7
#Mann= 3 , 0 , 0
       0     .04       0  110.23    .033       0   771.6     .04       0
Bank Sta=110.23,771.6
XS Rating Curve= 0 ,0
Exp/Cntr=0.3,0.1

Type RM Length L Ch R = 1 ,2713.343,133.2,108.04,79.26
XS GIS Cut Line= 2
      483867.538    3614361.6448     482987.3557    3614298.1447
#Sta/Elev= 30
       0 2084.23   27.58 2078.84   55.15 2074.91   82.73 2067.84  110.31 2045.34
  137.89 2028.35  165.46 2024.72  193.04 2018.04  220.62 2012.34  248.19 1991.13
  275.77 1974.77  303.35 1967.55   358.5 1947.44  414.98 1942.55  443.17 1942.92
  468.72 1942.19  496.39    1945  551.54 1945.43  579.12 1948.96   606.7 1953.69
  634.28 1955.34  661.85 1955.47  689.43 1957.42  717.01 1961.59  744.58 1968.13
  772.16 1977.21  799.74 1987.12  827.32    1995  854.89 2001.73  882.47 2011.37
#Mann= 3 , 0 , 0
       0     .04       0  220.62    .033       0  744.58     .04       0
Bank Sta=220.62,744.58
XS Rating Curve= 0 ,0
Exp/Cntr=0.3,0.1

Type RM Length L Ch R = 1 ,2605.305,62.78,61.97,56.14
XS GIS Cut Line= 2
     483869.3019    3614229.3529     482973.2445    3614234.6446
#Sta/Elev= 30
       0 2053.57      28 2060.89      56 2067.49   84.01 2077.65  112.01 2084.86
  140.01 2070.25  168.01 2059.39  196.02 2049.65  252.02 2029.78  280.02 2021.47
  308.03 2012.51  336.03 2000.83  364.03 1978.83  392.03  1960.6  420.03 1951.04
  448.04  1945.2  475.77 1943.28  503.96 1942.19  560.05    1945  588.05 1946.08
  616.05 1949.42  644.05 1954.54  672.05 1956.08  700.06 1956.88  728.06 1957.38
  756.06 1965.94  784.06 1975.02  812.07 1984.91  840.07 1997.59  896.07 2025.97
#Mann= 3 , 0 , 0
       0     .04       0  308.03    .033       0  840.07     .04       0
Bank Sta=308.03,840.07
XS Rating Curve= 0 ,0
Exp/Cntr=0.3,0.1

Type RM Length L Ch R = 1 ,2543.338,88.91,94.93,137.51
XS GIS Cut Line= 2
     483661.1626    3614174.6722     482975.0084    3614181.7278
#Sta/Elev= 28
       0 2043.35   27.45 2030.17    54.9 2019.55   82.34  2010.7  109.79 1999.26
  137.24 1981.23  164.69 1963.54  165.92 1963.14  192.13 1954.59  219.58  1950.1
  247.03 1945.59  274.48    1945   302.2 1943.83  329.34 1943.28  358.94 1942.19
  386.08 1943.28  415.68 1943.28  439.16 1945.92  466.61 1948.18  494.06  1951.1
   521.5 1952.25  548.95 1960.73  559.62 1963.74   576.4 1968.47  603.85 1979.57
   631.3 1993.55  658.74 2009.71  686.19 2024.69
#Mann= 3 , 0 , 0
       0     .04       0  109.79    .033       0   631.3     .04       0
Bank Sta=109.79,631.3
XS Rating Curve= 0 ,0
Exp/Cntr=0.3,0.1

Type RM Length L Ch R = 1 ,2448.404,105.46,222.93,185.16
XS GIS Cut Line= 3
     483611.7736    3614095.2971     483241.7378    3614107.1604
     482953.8417    3614038.8525
#Sta/Elev= 28
       0 2012.84   26.44 2003.17   52.89 1997.62   79.33 1992.66  105.78 1988.11
  132.22 1983.45  158.67 1978.85     169 1974.33  185.11 1967.26  211.56 1955.56
     238 1949.39  264.45 1947.79  290.89 1946.59  317.34 1945.33  342.91 1942.73
  369.43 1941.09  397.18 1941.37  424.32 1940.55  452.07 1942.19  477.82    1945
  504.72    1945  531.62 1953.29  558.52 1966.27  578.01 1976.79  585.42 1980.79
  612.32    2000  639.22 2020.84  666.11 2041.87
#Mann= 3 , 0 , 0
       0     .04       0  132.22    .033       0  612.32     .04       0
Bank Sta=132.22,612.32
XS Rating Curve= 0 ,0
Exp/Cntr=0.3,0.1

Type RM Length L Ch R = 1 ,2225.478,103.01,233.75,253.21
XS GIS Cut Line= 3
     483643.5237    3614015.9219     483134.3257    3613927.5655
     482929.1472    3613839.5327
#Sta/Elev= 30
       0 2007.17    27.2 1998.94    54.4 1990.17    81.6 1983.87   108.8 1978.76
     136 1974.85   163.2 1970.92   190.4 1969.63  207.25 1967.95   217.6 1966.91
   244.8 1964.58     272 1962.59   299.2 1960.21   326.4 1957.55   353.6 1954.32
  380.81 1951.05  408.01 1948.78  435.59 1947.49  461.67 1946.38  488.46 1942.55
  515.95 1940.32   553.3 1941.44  575.15 1946.86  600.53 1960.34  628.44 1969.57
  639.57  1973.3  656.35 1978.91  684.26 1986.99  712.17 1993.22  740.07  1998.4
#Mann= 3 , 0 , 0
       0     .04       0  207.25    .033       0  639.57     .04       0
Bank Sta=207.25,639.57
XS Rating Curve= 0 ,0
Exp/Cntr=0.3,0.1

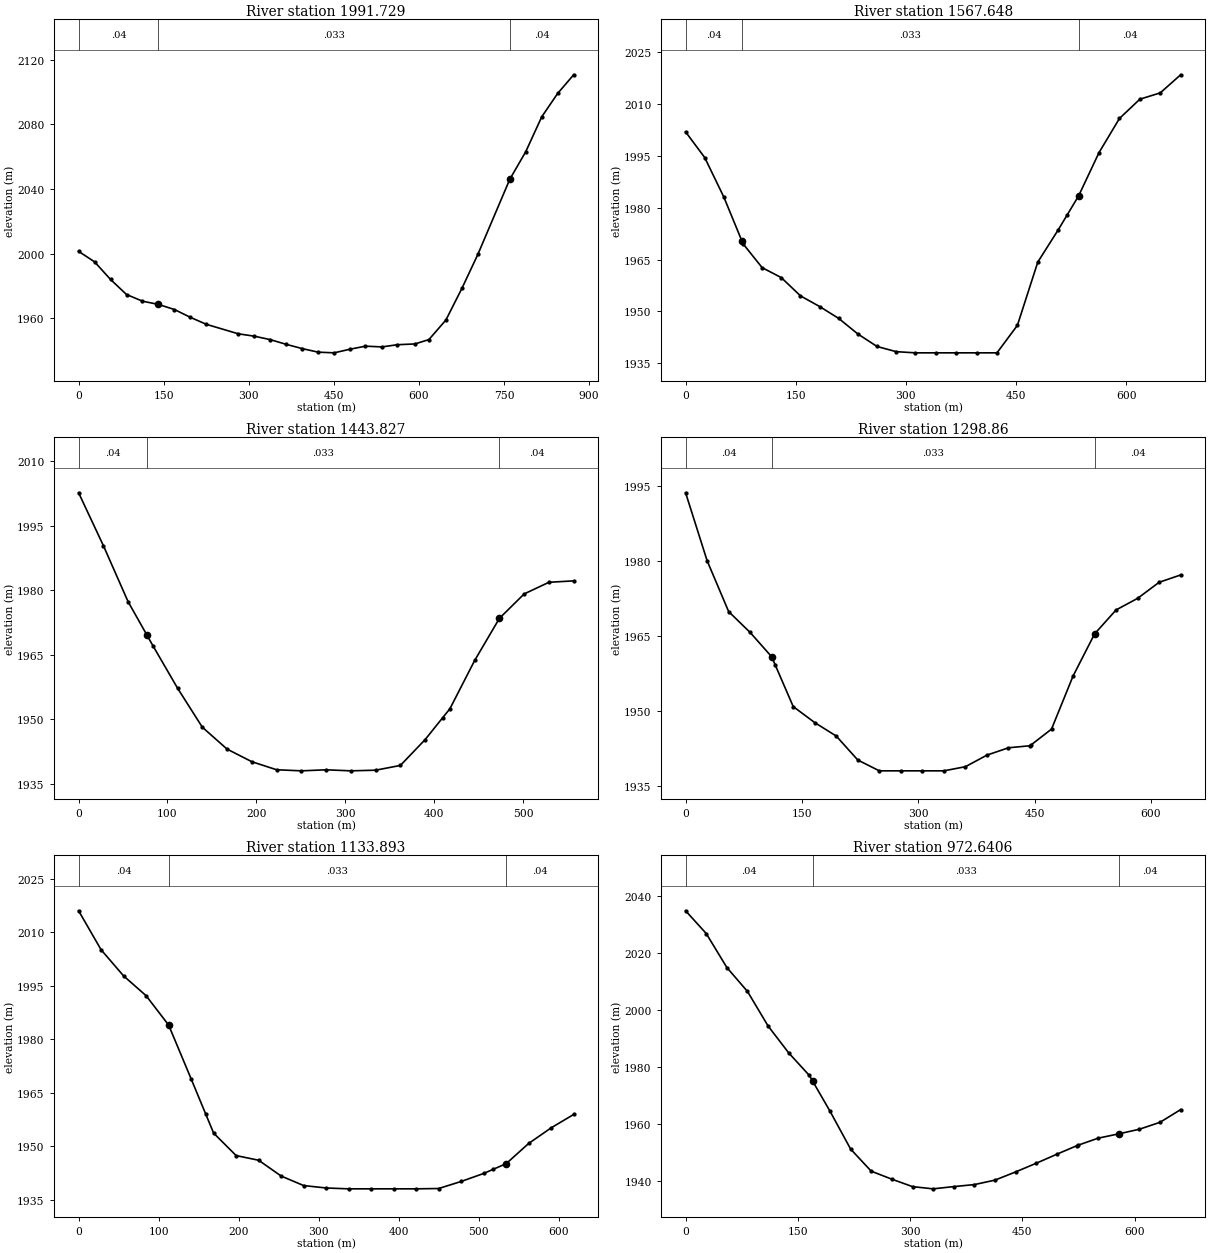
Type RM Length L Ch R = 1 ,1991.729,89.17,424.08,465.38
XS GIS Cut Line= 2
     483668.2182     3613998.283     482920.3278    3613548.4904
#Sta/Elev= 30
       0 2001.46   28.15 1994.97   56.31 1984.06   84.46 1974.75  112.61 1970.63
  140.76 1968.62  168.92 1965.46  197.07 1960.62  225.22  1956.3  281.53 1950.43
  309.68 1948.96  337.83 1946.83  365.98 1943.91  394.14 1941.28  422.29 1939.07
  450.44 1938.65   479.3 1940.96  505.73 1942.78   534.8 1942.32  562.11 1943.69
  592.95 1944.15  617.62 1946.88  647.51 1958.98  675.66 1978.52  703.81 1999.57
  760.12 2046.07  788.27 2063.17  816.42 2084.73  844.57 2099.23  872.73 2110.75
#Mann= 3 , 0 , 0
       0     .04       0  140.76    .033       0  760.12     .04       0
Bank Sta=140.76,760.12
XS Rating Curve= 0 ,0
Exp/Cntr=0.3,0.1

Type RM Length L Ch R = 1 ,1567.648,89.94,123.82,237.59
XS GIS Cut Line= 3
      483719.371    3614001.8108     483618.8084    3613705.5599
     483400.1065    3613417.9624
#Sta/Elev= 28
       0 2001.96   26.07 1994.51   52.14 1983.06   76.89 1970.26   78.21 1969.57
  104.28 1962.65  130.36 1959.77  156.43 1954.49   182.5 1951.41  208.57 1947.95
  234.64 1943.45  260.71 1939.84  286.78 1938.34  312.85    1938  340.65    1938
  368.44    1938  396.23    1938  424.03    1938  451.82 1945.95  479.61 1964.27
   507.4 1973.59  519.54 1977.89   535.2 1983.43  562.99 1995.96  590.78 2005.83
  618.58 2011.41  646.37 2013.24  674.16 2018.48
#Mann= 3 , 0 , 0
       0     .04       0   76.89    .033       0   535.2     .04       0
Bank Sta=76.89,535.2
XS Rating Curve= 0 ,0
Exp/Cntr=0.3,0.1

Type RM Length L Ch R = 1 ,1443.827,183.01,144.97,95.39
XS GIS Cut Line= 2
     483805.8018    3614008.8664     483668.2182    3613469.1153
#Sta/Elev= 23
       0 2002.71   27.85 1990.42    55.7 1977.35   76.65 1969.67   83.55 1967.14
   111.4 1957.21  139.25 1948.14   167.1 1943.05  194.95 1940.12   222.8 1938.25
  250.65    1938  278.51 1938.24  306.36    1938  334.21 1938.15  362.06 1939.26
  389.91 1945.28  409.53 1950.34  417.76 1952.45  445.61 1963.68  473.46 1973.49
  501.31 1979.17  529.16 1981.88  557.01 1982.21
#Mann= 3 , 0 , 0
       0     .04       0   76.65    .033       0  473.46     .04       0
Bank Sta=76.65,473.46
XS Rating Curve= 0 ,0
Exp/Cntr=0.3,0.1

Type RM Length L Ch R = 1 ,1298.86 ,256.19,164.97,69.39
XS GIS Cut Line= 2
     484005.1216    3614042.3803     483714.0794     3613474.407
#Sta/Elev= 26
       0 1993.73   27.75 1980.11    55.5 1969.92   83.24 1965.73  110.99 1960.86
  115.55 1959.22  138.74 1950.88  166.49 1947.67  194.23 1944.97  221.98 1940.17
  249.73    1938  277.48    1938  305.23    1938  332.97    1938  360.72 1938.83
  388.47 1941.15  416.22 1942.62  443.97 1943.03  445.89 1943.26  471.71 1946.36
  499.46 1956.99  527.21 1965.44  554.96 1970.25   582.7 1972.57  610.45 1975.79
   638.2 1977.26
#Mann= 3 , 0 , 0
       0     .04       0  110.99    .033       0  527.21     .04       0
Bank Sta=110.99,527.21
XS Rating Curve= 0 ,0
Exp/Cntr=0.3,0.1

Type RM Length L Ch R = 1 ,1133.893,266.7,161.25,64.77
XS GIS Cut Line= 2
     484273.2333    3613957.7135     483811.0934    3613546.7265
#Sta/Elev= 25
       0 2015.99   28.11 2005.05   56.22 1997.72   84.33 1992.17  112.45 1983.94
  140.56 1968.85   158.8 1958.97  168.67 1953.63  196.78 1947.33  224.89 1946.02
     253 1941.59  281.11 1938.92  309.23 1938.24  337.34    1938  365.45    1938
  393.56    1938  421.67    1938  449.78 1938.09   477.9 1940.07  506.01 1942.31
  517.94 1943.48  534.12 1945.06  562.23 1950.73  590.34 1955.11  618.45 1958.86
#Mann= 3 , 0 , 0
       0     .04       0  112.45    .033       0  534.12     .04       0
Bank Sta=112.45,534.12
XS Rating Curve= 0 ,0
Exp/Cntr=0.3,0.1

Type RM Length L Ch R = 1 ,972.6406,163.62,130.61,87.27
XS GIS Cut Line= 2
     484414.3446    3613705.4769     483789.9267    3613486.7542
#Sta/Elev= 27
       0 2034.67   27.57  2026.7   55.13 2014.79    82.7  2006.4  110.27 1994.28
  137.84 1984.85   165.4 1976.95  170.05 1974.84  192.97 1964.44  220.54 1951.16
  248.11  1943.4  275.67  1940.6  303.24    1938  330.57 1937.22  358.38    1938
  385.94 1938.71  413.51 1940.28  441.08 1943.15  468.65 1946.19  496.21 1949.36
  522.92 1952.35  523.78 1952.44  551.35 1954.98  578.92 1956.49  606.48 1958.11
  634.05 1960.54  661.62 1964.99
#Mann= 3 , 0 , 0
       0     .04       0  170.05    .033       0  578.92     .04       0
Bank Sta=170.05,578.92
XS Rating Curve= 0 ,0
Exp/Cntr=0.3,0.1

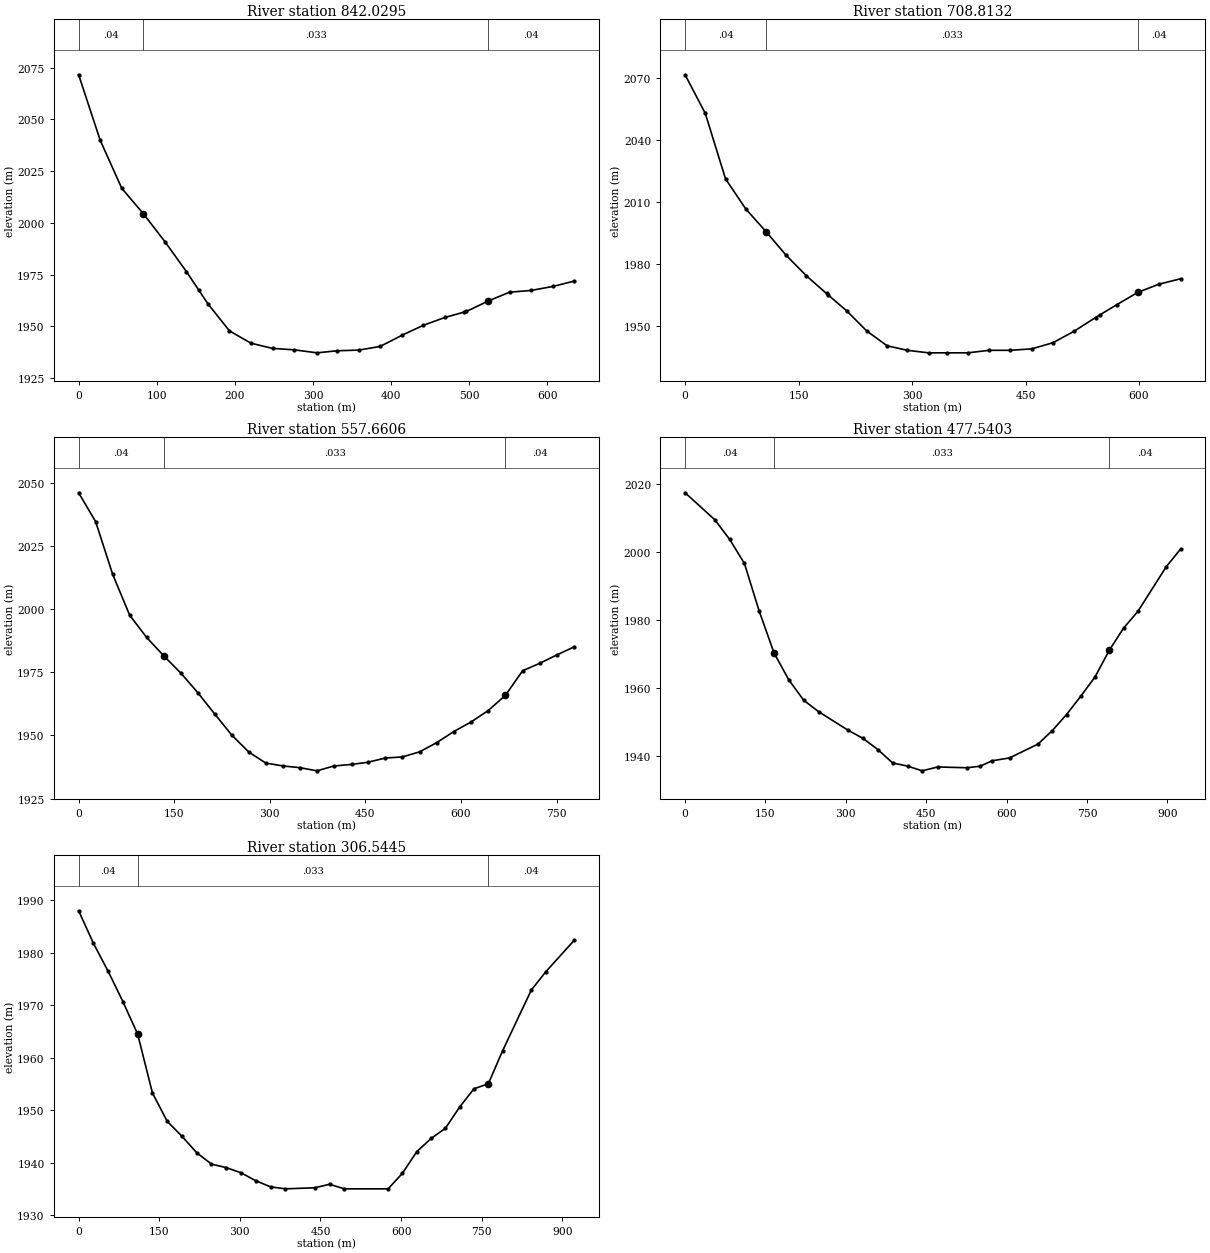
Type RM Length L Ch R = 1 ,842.0295,130.06,133.22,64.24
XS GIS Cut Line= 2
     484389.6502    3613525.5598     483765.2322    3613414.4346
#Sta/Elev= 26
       0 2071.55   27.58 2039.93   55.15  2016.7   82.73 2004.43   110.3 1990.95
  137.88 1976.44  153.87  1967.4  165.45 1960.84  193.03 1947.76   220.6 1941.78
  248.18 1939.28  275.68 1938.59  305.29 1937.13   330.9 1938.14  358.48 1938.45
  386.05 1940.24  413.63 1945.58   441.2 1950.45  468.78 1954.24  493.66 1956.86
  496.35 1957.14  523.93 1962.14   551.5 1966.45  579.08  1967.3  606.65  1969.2
  634.23 1971.82
#Mann= 3 , 0 , 0
       0     .04       0   82.73    .033       0  523.93     .04       0
Bank Sta=82.73,523.93
XS Rating Curve= 0 ,0
Exp/Cntr=0.3,0.1

Type RM Length L Ch R = 1 ,708.8132,113.88,151.15,113.57
XS GIS Cut Line= 3
     484405.5252    3613393.2679     484033.7108    3613354.1871
      483752.885    3613368.5734
#Sta/Elev= 27
       0 2071.71    26.7 2052.96   53.41 2021.23   80.11 2006.64  106.82 1995.65
  133.52 1984.13  160.23 1974.19  186.93 1965.57  189.33 1964.81  213.64 1957.14
  240.34 1947.32  267.04 1940.19  293.75    1938  321.94 1936.77  345.99 1936.77
  373.74 1936.77  401.98    1938   430.1    1938  458.22  1938.7  486.34 1941.69
  514.46  1947.3  542.58 1953.91  548.14 1955.14   570.7 1960.15  598.82 1966.19
  626.94 1970.15  655.06 1972.72
#Mann= 3 , 0 , 0
       0     .04       0  106.82    .033       0  598.82     .04       0
Bank Sta=106.82,598.82
XS Rating Curve= 0 ,0
Exp/Cntr=0.3,0.1

Type RM Length L Ch R = 1 ,557.6606,98.92,80.12,85.94
XS GIS Cut Line= 3
     484419.6363    3613289.1983      483998.066    3613220.4064
     483652.3431    3613278.6149
#Sta/Elev= 30
       0 2046.01    26.7 2034.58   53.39 2013.76   80.09 1997.55  106.79 1988.74
  133.48  1981.5  160.18  1974.7  186.88 1966.94  213.57 1958.45  240.27 1950.13
  266.97  1943.4  293.66 1939.03  321.41 1937.86  346.78 1937.22  374.27 1935.95
  400.35 1937.86  428.55  1938.5  454.11 1939.35  481.08 1941.01  508.05 1941.46
  535.02 1943.45  561.99 1947.12  588.96 1951.52  615.92 1955.29  642.89 1959.83
  669.86 1965.85  696.83 1975.57   723.8 1978.53  750.77 1981.85  777.73 1985.02
#Mann= 3 , 0 , 0
       0     .04       0  133.48    .033       0  669.86     .04       0
Bank Sta=133.48,669.86
XS Rating Curve= 0 ,0
Exp/Cntr=0.3,0.1

Type RM Length L Ch R = 1 ,477.5403,99.34,171,282.72
XS GIS Cut Line= 3
     484504.3032    3613202.7675      483982.191    3613142.7952
     483587.0791    3613199.2397
#Sta/Elev= 30
       0 2017.48   55.32 2009.54   82.98 2003.78  110.64 1996.66   138.3 1982.57
  165.96 1970.25  193.62 1962.29  221.28 1956.32  248.94 1952.95  304.26 1947.45
  331.92 1945.06  359.58 1941.78  387.24 1937.81  415.86 1936.86  442.29 1935.49
  471.37 1936.63  525.99  1936.4  550.66 1936.86  572.69 1938.45  605.37  1939.3
  658.59 1943.39  685.19 1947.36   711.8  1952.1  738.41 1957.51  765.02 1963.21
  791.63 1971.07  818.24 1977.58  844.84  1982.5  898.06 1995.72  924.67  2000.9
#Mann= 3 , 0 , 0
       0     .04       0  165.96    .033       0  791.63     .04       0
Bank Sta=165.96,791.63
XS Rating Curve= 0 ,0
Exp/Cntr=0.3,0.1

Type RM Length L Ch R = 1 ,306.5445,111.43,306.54,346.71
XS GIS Cut Line= 3
      484490.192    3613139.2674     483961.5182     3612990.148
     483620.5931    3612839.4057
#Sta/Elev= 30
       0 1987.96   27.47 1981.78   54.93 1976.43    82.4 1970.66  109.86 1964.46
  137.33 1953.25  164.79 1947.87  192.26 1945.01  219.72 1941.88  247.19 1939.71
  274.65 1939.04  302.12 1938.06  329.58 1936.54  357.05 1935.38  384.51    1935
  439.44  1935.2  466.91 1935.87  494.37    1935  575.93    1935  602.55 1937.97
  629.18 1942.08  655.81 1944.59  682.43 1946.53  709.06 1950.59  735.68 1954.07
  762.31    1955  788.94 1961.31  842.19 1972.84  868.81 1976.29  922.07 1982.33
#Mann= 3 , 0 , 0
       0     .04       0  109.86    .033       0  762.31     .04       0
Bank Sta=109.86,762.31
XS Rating Curve= 0 ,0
Exp/Cntr=0.3,0.1

Chan Stop Cuts=-1
Use User Specified Reach Order=0
Composite Channel Slope=5